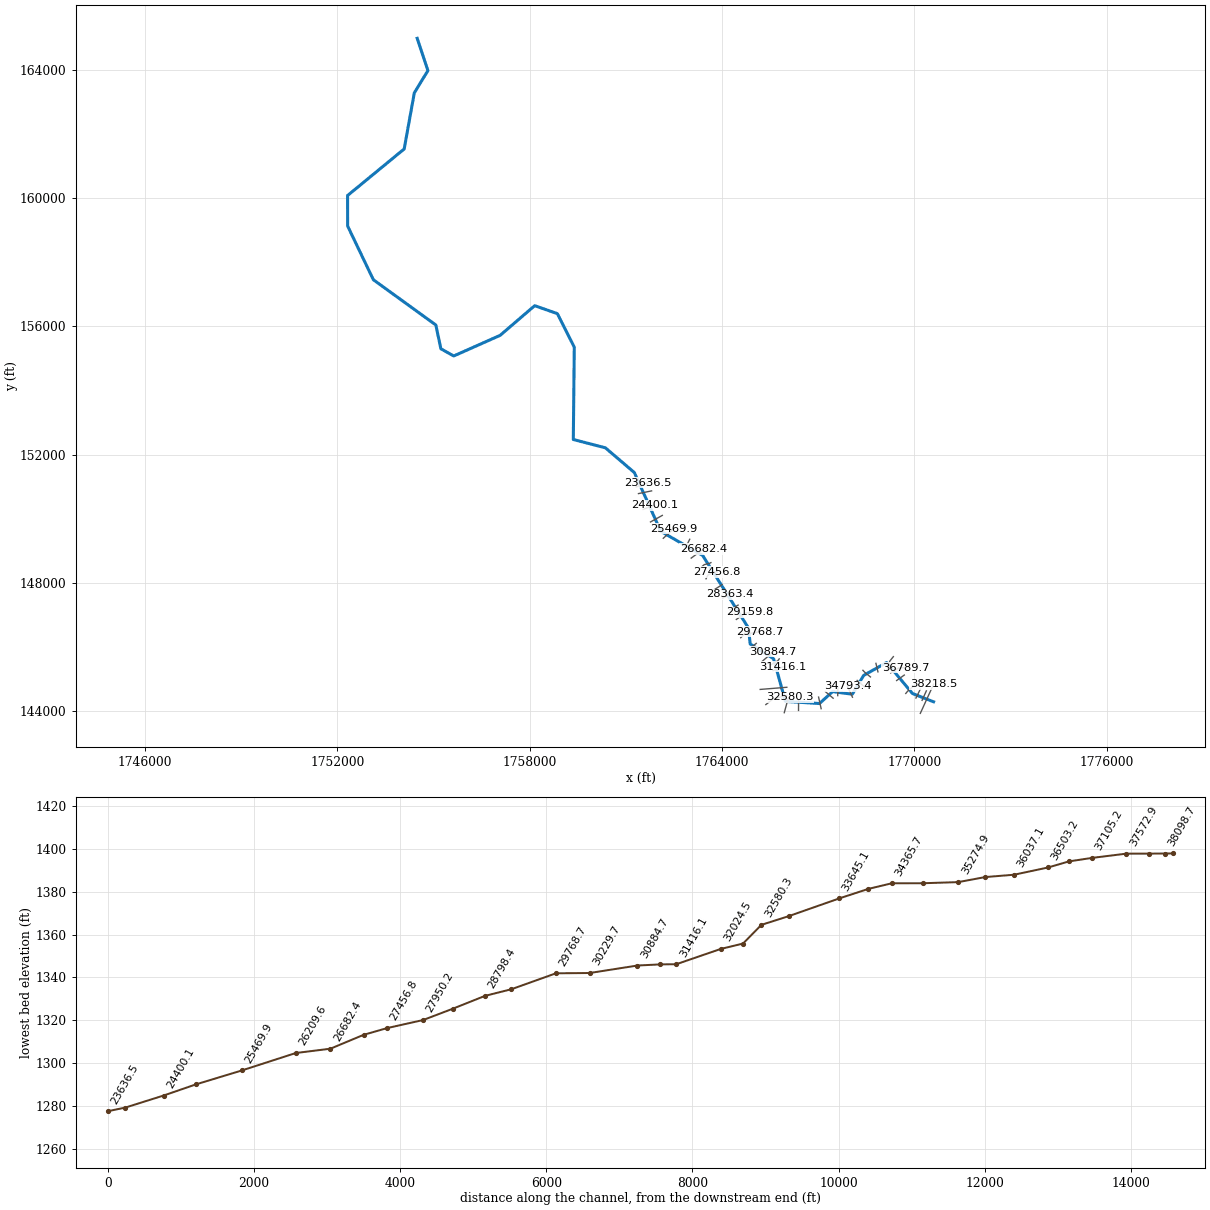
--- Clear Fork A.prj (project) ---

Proj Title=Clear Fork A
Current Plan=p01
Default Exp/Contr=0,0
English Units
Geom File=g01
Flow File=f01
Plan File=p01
BEGIN DESCRIPTION:
END DESCRIPTION:
DSS Export Rating Curves= 0
DSS Export Rating Curve Sorted= 0
DSS Export Volume Flow Curves= 0
DXF OffsetX= 0
DXF OffsetY= 0
DXF ScaleX= 0
DXF ScaleY= 0

--- Clear Fork A.p01 (plan) ---

Plan Title=Floodplain
Program Version=4.00
Geom File=g01
Flow File=f01
K Sum by GR=0
Std Step Tol=0.01
Critical Tol=0.01
Num of Std Step Trials=20
Max Error Tol=0.3
Flow Tol Ratio=0.001
Split Flow NTrial=30
Split Flow Tol=0.02
Split Flow Ratio=0.02
Log Output Level=0
Friction Slope Method=1
Unsteady Friction Slope Method=2
Unsteady Bridges Friction Slope Method=1
Global Log Level=0
CheckData=False
Run HTab=0
Run UNet=0
Run PostProcess=0
UNET Theta=0
UNET Theta Warmup=0
UNET ZTol=0
UNET ZSATol=0
UNET MxIter=0
UNET MaxInSteps=0
UNET DtIC=0
UNET DtMin=0
UNET MaxCRTS=0
UNET WFStab=0
UNET SFStab=0
UNET WFX=0
UNET SFX=0
UNET DSS MLevel=0
UNET DZMax Abort=0
UNET Convert EG Bridges=0
UNET Use Existing IB Tables=0
UNET Froude Limit=0
UNET Froude Power=0
Write IC File=0
Echo Input=False
Echo Output=False
Write Detailed=0

--- Clear Fork A.f01 (steady flow) ---

Flow Title=NFF Regression Equation
Program Version=4.00
Number of Profiles=1
Profile Names=P100yr
River Rch & RM=Clear Fork A,Main      ,38218.5
2769.935
River Rch & RM=Clear Fork A,Main      ,36503.2
3060.253
River Rch & RM=Clear Fork A,Main      ,32329.2
3116.571
River Rch & RM=Clear Fork A,Main      ,32024.5
3693.907
River Rch & RM=Clear Fork A,Main      ,27136.4
4077.418
River Rch & RM=Clear Fork A,Main      ,17541.1
4440.060
Boundary for River Rch & Prof#=Clear Fork A,Main      ,1
Up Type=0
Dn Type=3
Dn Slope=0.010251

--- Clear Fork A.g01 (geometry) ---

Geom Title=Geometry
Program Version=4.00

River Reach=Clear Fork A    ,Main
Reach XY= 30
     1770602.229      144286.787     1769944.436      144546.117
     1769135.469      145511.029     1768422.886      145111.419
     1768066.293       144523.65     1767452.559      144604.597
     1767043.259      144233.203     1765979.742      144299.204
      1765611.49      145630.499     1764882.774      146089.166
     1764826.271      146591.873     1763398.852      148852.021
     1762092.567      149604.419     1761267.984      151438.215
     1760364.274      152210.047     1759363.756      152469.439
     1759394.246      155349.503     1758866.277      156396.163
     1758159.832      156643.918     1757082.599      155719.385
     1755633.731      155075.173     1755232.609      155298.917
      1755075.28      156041.444     1753126.264      157453.231
     1752323.316      159129.882     1752322.504       160081.07
     1754088.109       161532.31     1754403.889      163282.966
     1754828.182      163977.712     1754493.608      164983.854

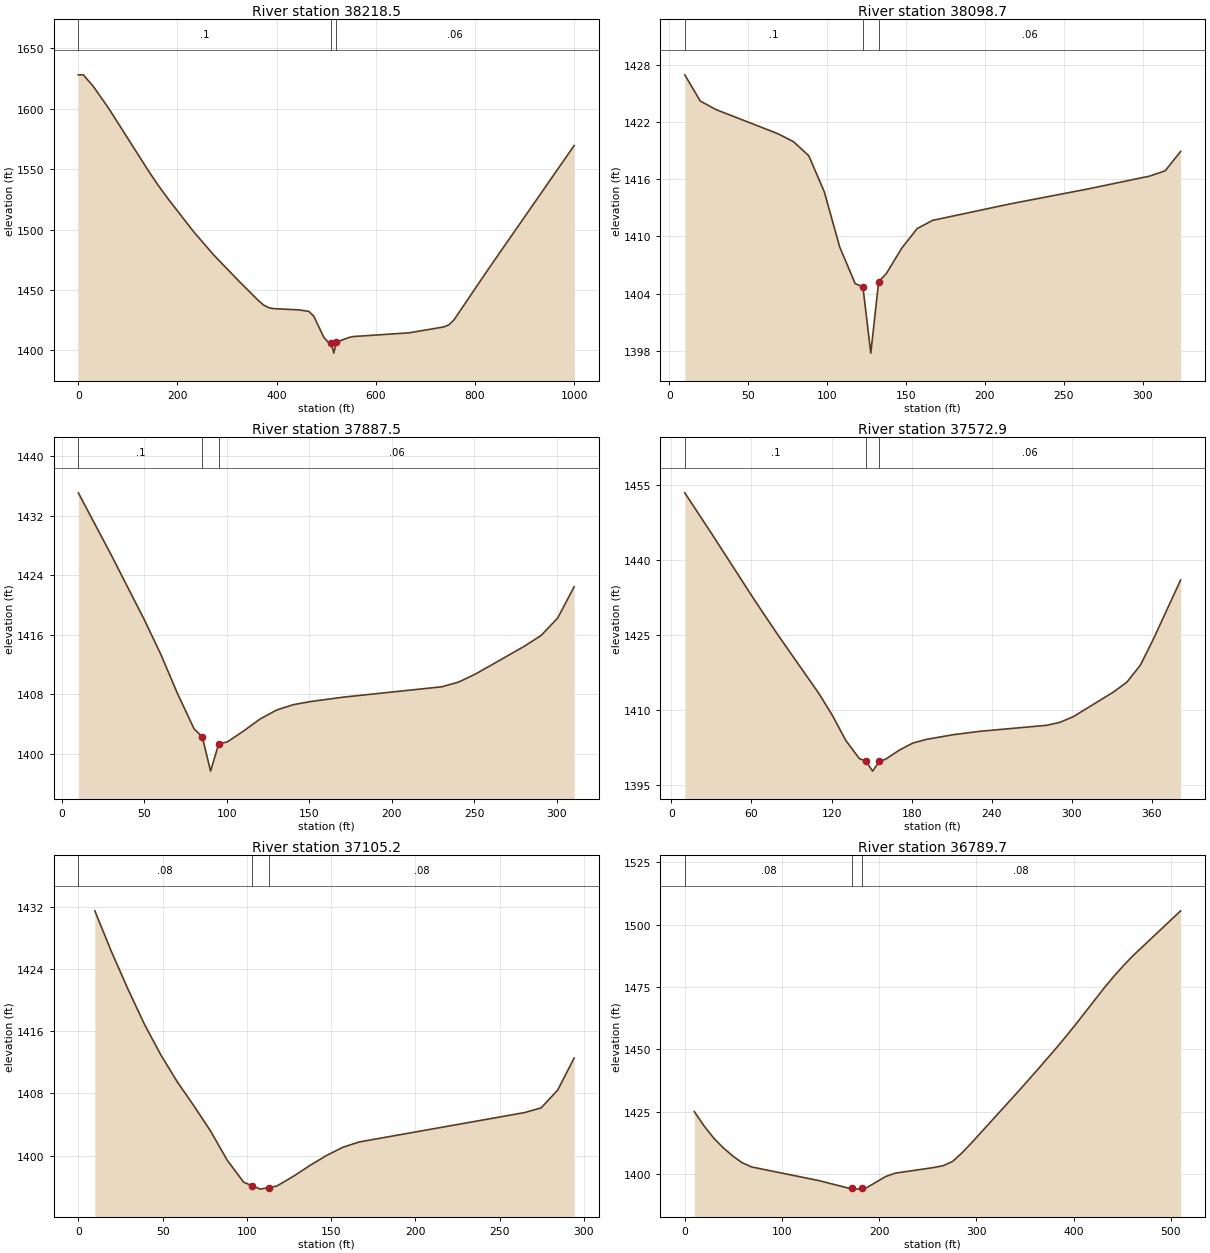
Type RM Length L Ch R = 1 ,38218.5 ,119.6,119.7,119.9
XS GIS Cut Line= 2
     1770188.495      143925.949     1770603.654      144835.715
#Sta/Elev= 30
       0 1628.08    10.1 1628.08    30.3 1618.46    60.6 1600.73   141.4 1548.64
   161.6 1536.37   181.8 1525.06   232.3 1498.41   272.7  1479.2   323.2 1457.67
   363.6 1441.14   373.7 1437.58   383.8 1435.47   393.9 1434.62   444.5  1433.6
   464.7 1432.37   474.8 1428.42     495 1411.01   505.1 1406.24   510.2 1406.16
   515.2  1397.8   520.2 1406.76   545.5 1410.73   555.6 1411.56   666.7 1414.57
   737.4 1419.49   747.5 1421.27   757.6 1425.28   828.3 1468.13    1000 1569.57
#Mann= 3 , 0 , 0
       0      .1       0   510.2    .045       0   520.2     .06       0
Bank Sta=510.2,520.2
XS Rating Curve= 0 ,0
Exp/Cntr=0.3,0.1

Type RM Length L Ch R = 1 ,38098.7 ,211.9,211.2,210.5
XS GIS Cut Line= 2
     1770244.033      144332.572      1770376.65      144628.271
#Sta/Elev= 21
     9.8 1426.95    19.6  1424.2    29.5 1423.31    68.7 1420.78    78.6 1419.95
    88.4 1418.46    98.2 1414.69     108 1408.89   117.8 1405.04   122.7 1404.72
   127.7 1397.75   132.7 1405.25   137.5 1406.08   147.3 1408.76   157.1 1410.82
   166.9 1411.68   216.1 1413.41   265.2 1414.97   304.4 1416.32   314.3 1416.88
   324.1 1418.91
#Mann= 3 , 0 , 0
     9.8      .1       0   122.7    .045       0   132.7     .06       0
Bank Sta=122.7,132.7
XS Rating Curve= 0 ,0
Exp/Cntr=0.3,0.1

Type RM Length L Ch R = 1 ,37887.5 ,322.5,314.7,306.8
XS GIS Cut Line= 2
     1770052.163      144404.258     1770189.619      144682.936
#Sta/Elev= 24
      10 1435.08    30.1 1426.67    50.1    1418    60.1 1413.35    70.2 1408.09
    80.2 1403.38    85.2 1402.29    90.2  1397.7    95.2  1401.4   100.2  1401.6
   110.3  1403.1   120.3 1404.71   130.3 1405.91   140.3 1406.62   150.4 1407.03
   170.4 1407.63   230.5 1409.03   240.6 1409.66   250.6 1410.71   260.6 1411.96
   280.7  1414.5   290.7 1415.93   300.7 1418.26   310.7 1422.47
#Mann= 3 , 0 , 0
      10      .1       0    85.2    .045       0    95.2     .06       0
Bank Sta=85.2,95.2
XS Rating Curve= 0 ,0
Exp/Cntr=0.3,0.1

Type RM Length L Ch R = 1 ,37572.9 ,469.6,467.7,465.7
XS GIS Cut Line= 3
     1769734.606      144547.182     1769792.315      144617.033
     1770010.738      144809.094
#Sta/Elev= 26
    10.1 1453.43    30.2 1445.26    60.4 1432.74    70.5 1428.68    80.5 1424.72
   110.7 1413.17   120.7 1408.82   130.7 1403.83   140.8  1400.2   145.8 1399.66
   150.8 1397.68   155.8 1399.61   160.8 1400.11   170.8 1401.89   180.9  1403.3
   190.9 1404.03     211 1404.97     231 1405.65   281.2 1406.86   291.2 1407.46
   301.2  1408.6   331.3 1413.54   341.3 1415.52   351.4 1418.93   361.4  1424.3
   381.5 1435.96
#Mann= 3 , 0 , 0
    10.1      .1       0   145.8    .045       0   155.8     .06       0
Bank Sta=145.8,155.8
XS Rating Curve= 0 ,0
Exp/Cntr=0.3,0.1

Type RM Length L Ch R = 1 ,37105.2 ,315.2,315.5,315.3
XS GIS Cut Line= 2
     1769449.617      144950.316     1769688.753      145121.665
#Sta/Elev= 23
     9.8 1431.45    19.6 1426.23    29.4 1421.42    39.2 1416.89      49 1412.93
    58.8 1409.46    68.6  1406.4    78.5 1403.16    88.3 1399.44    98.1  1396.6
   102.9 1396.16   107.9 1395.71   112.9 1395.91   117.7  1396.1   127.5 1397.34
   137.3 1398.73   147.1 1400.01   156.9 1401.08   166.7 1401.77   264.8 1405.54
   274.6 1406.14   284.4 1408.42   294.2 1412.55
#Mann= 3 , 0 , 0
       0     .08       0   102.9    .045       0   112.9     .08       0
Bank Sta=102.9,112.9
XS Rating Curve= 0 ,0
Exp/Cntr=0.3,0.1

Type RM Length L Ch R = 1 ,36789.7 ,271.5,286.6,301.7
XS GIS Cut Line= 3
     1769261.955       145187.41     1769504.223      145338.205
     1769728.295      145355.151
#Sta/Elev= 30
     9.8 1425.12    19.7 1419.47    29.5 1414.62    39.4 1410.69    49.2 1407.41
      59 1404.65    68.9 1402.94   137.8 1397.51   167.3  1394.6   172.1 1394.35
   177.1 1394.08   182.1 1394.37     187 1394.64   206.6 1399.11   216.5 1400.47
   255.8 1402.71   265.7 1403.45   275.5 1405.15   285.4 1408.67   295.1 1412.64
     344 1433.59   363.5 1442.18   383.1 1451.01   392.8 1455.56   402.6 1460.28
   431.9 1474.86   441.7 1479.43   451.5 1483.68   461.2 1487.59   510.1 1505.53
#Mann= 3 , 0 , 0
       0     .08       0   172.1    .045       0   182.1     .08       0
Bank Sta=172.1,182.1
XS Rating Curve= 0 ,0
Exp/Cntr=0.3,0.1

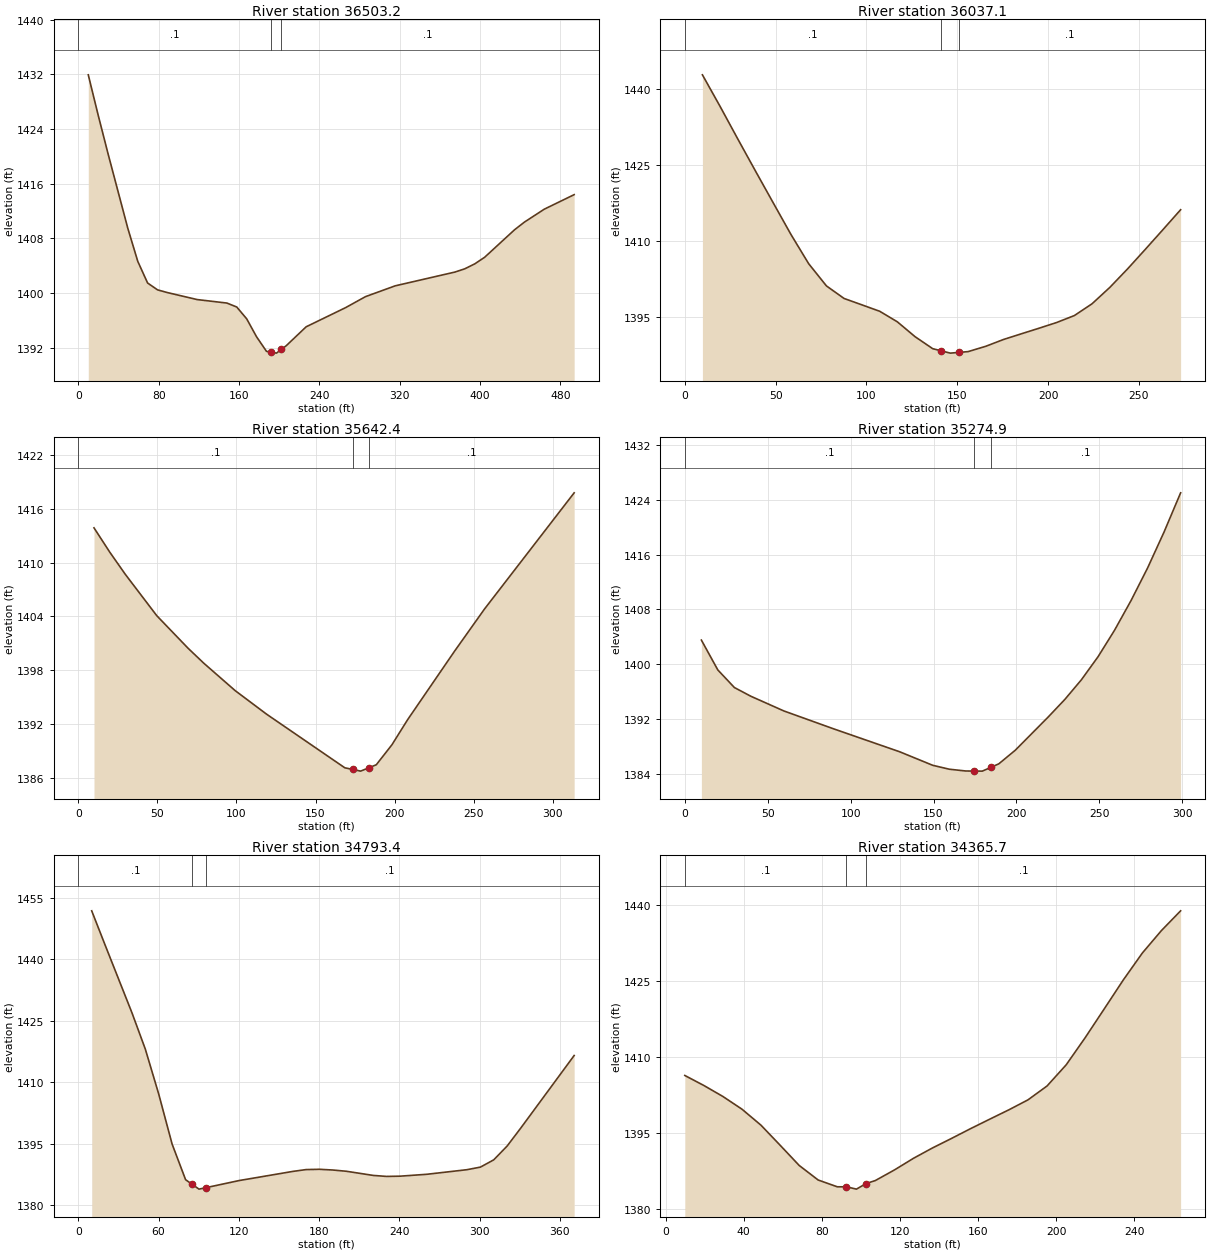
Type RM Length L Ch R = 1 ,36503.2 ,456.6,466,473.3
XS GIS Cut Line= 3
     1769142.696      145255.355     1769236.843      145556.628
     1769347.938      145695.967
#Sta/Elev= 30
     9.9 1431.93    19.7 1426.07    29.6 1420.39    49.3 1409.48    59.2 1404.66
      69 1401.49    78.9 1400.49    88.8 1400.09   118.4 1399.07     148 1398.56
   157.8 1397.98   167.7 1396.25   177.5 1393.63   187.4  1391.5   192.3 1391.37
   197.3 1391.24   202.3  1391.8   207.1 1392.33   226.9 1395.09   266.3  1397.9
     286  1399.5   315.6 1401.08     375 1403.09   384.9 1403.57   394.8 1404.29
   404.7 1405.26   434.4 1409.27   444.3  1410.4   464.1 1412.29   493.8 1414.41
#Mann= 3 , 0 , 0
       0      .1       0   192.3    .045       0   202.3      .1       0
Bank Sta=192.3,202.3
XS Rating Curve= 0 ,0
Exp/Cntr=0.3,0.1

Type RM Length L Ch R = 1 ,36037.1 ,381.7,394.7,407.7
XS GIS Cut Line= 3
     1768867.259      145220.931     1768835.888      145353.778
     1768804.517      145486.624
#Sta/Elev= 30
     9.7  1442.9    19.5 1436.61    29.2  1430.2      39 1423.82    48.8 1417.51
    58.5  1411.3    68.2 1405.55      78 1401.15    87.7 1398.67    97.5 1397.41
   107.3 1396.14     117 1394.06   126.8 1391.11   136.5 1388.74   141.2 1388.31
   146.2 1387.86   151.2 1388.01     156 1388.16   165.7 1389.21   175.5 1390.56
   185.3 1391.68     195 1392.78   204.7 1393.91   214.5 1395.29   224.2 1397.61
     234 1400.85   243.8 1404.52   253.5 1408.36   263.3 1412.29     273 1416.22
#Mann= 3 , 0 , 0
       0      .1       0   141.2    .045       0   151.2      .1       0
Bank Sta=141.2,151.2
XS Rating Curve= 0 ,0
Exp/Cntr=0.3,0.1

Type RM Length L Ch R = 1 ,35642.4 ,368.8,367.6,366.4
XS GIS Cut Line= 3
     1768632.922      145061.962     1768450.127      145214.292
     1768398.411      145269.432
#Sta/Elev= 18
     9.9 1413.88    19.8 1411.19    29.7  1408.7    49.6 1404.09    69.4 1400.46
    79.3  1398.8    99.1 1395.75     119 1393.12   168.5 1387.14   173.5 1386.96
   178.5 1386.77   183.5 1387.13   188.4 1387.48   198.3 1389.71   208.2  1392.5
   237.9 1400.14   256.8 1404.83   313.5 1417.78
#Mann= 3 , 0 , 0
       0      .1       0   173.5    .045       0   183.5      .1       0
Bank Sta=173.5,183.5
XS Rating Curve= 0 ,0
Exp/Cntr=0.3,0.1

Type RM Length L Ch R = 1 ,35274.9 ,489.2,481.5,473.8
XS GIS Cut Line= 2
     1768444.119      144758.254     1768218.164      144954.082
#Sta/Elev= 24
      10 1403.53    19.9 1399.18    29.9 1396.61    39.9 1395.33    59.8 1393.19
    89.7 1390.59   129.6 1387.24   149.5 1385.27   159.5  1384.7   169.4 1384.44
   174.4 1384.43   179.4 1384.42   184.4 1384.95   189.4 1385.49   199.3 1387.47
   219.3 1392.35   229.2 1394.88   239.2 1397.75   249.2  1401.1   259.1 1404.94
   269.1 1409.29   279.1 1414.05     289 1419.28     299    1425
#Mann= 3 , 0 , 0
       0      .1       0   174.4    .045       0   184.4      .1       0
Bank Sta=174.4,184.4
XS Rating Curve= 0 ,0
Exp/Cntr=0.3,0.1

Type RM Length L Ch R = 1 ,34793.4 ,436.1,427.7,418.9
XS GIS Cut Line= 2
     1768072.181      144430.029     1767916.837      144766.608
#Sta/Elev= 26
      10 1451.82      20 1443.49    40.1 1426.93    50.1 1418.06    60.1 1407.11
    70.1 1394.91    80.2  1386.2    85.2 1385.05    90.2  1383.9    95.2 1384.24
   120.2 1385.99   160.3 1388.22   170.3 1388.67   180.3 1388.74   190.4 1388.56
   200.4 1388.26   220.4 1387.25   230.4    1387   240.5 1387.06   260.5 1387.52
   290.5 1388.64   300.6 1389.27   310.6 1391.05   320.6 1394.42   330.6 1398.72
   370.7 1416.51
#Mann= 3 , 0 , 0
       0      .1       0    85.2    .045       0    95.2      .1       0
Bank Sta=85.2,95.2
XS Rating Curve= 0 ,0
Exp/Cntr=0.3,0.1

Type RM Length L Ch R = 1 ,34365.7 ,306.5,323.8,341.6
XS GIS Cut Line= 2
     1767612.112      144480.209     1767616.819      144743.823
#Sta/Elev= 29
     9.8 1406.34    19.5 1404.37    29.3 1402.19    39.1 1399.67    48.8 1396.52
    58.6 1392.56    68.4 1388.55    78.1 1385.68    87.9 1384.34    92.6 1384.34
    97.7 1383.88   102.6 1384.97   107.4 1385.58   117.2 1387.68   126.9 1389.97
   136.7 1392.03   146.5 1393.92   156.2 1395.84     166 1397.71   175.8 1399.56
   185.5 1401.51   195.3 1404.26   205.1 1408.44   214.8 1413.79   224.6  1419.5
   234.4 1425.24   244.1 1430.53   253.9 1434.98   263.7 1438.87
#Mann= 3 , 0 , 0
     9.8      .1       0    92.6    .045       0   102.6      .1       0
Bank Sta=92.6,102.6
XS Rating Curve= 0 ,0
Exp/Cntr=0.3,0.1

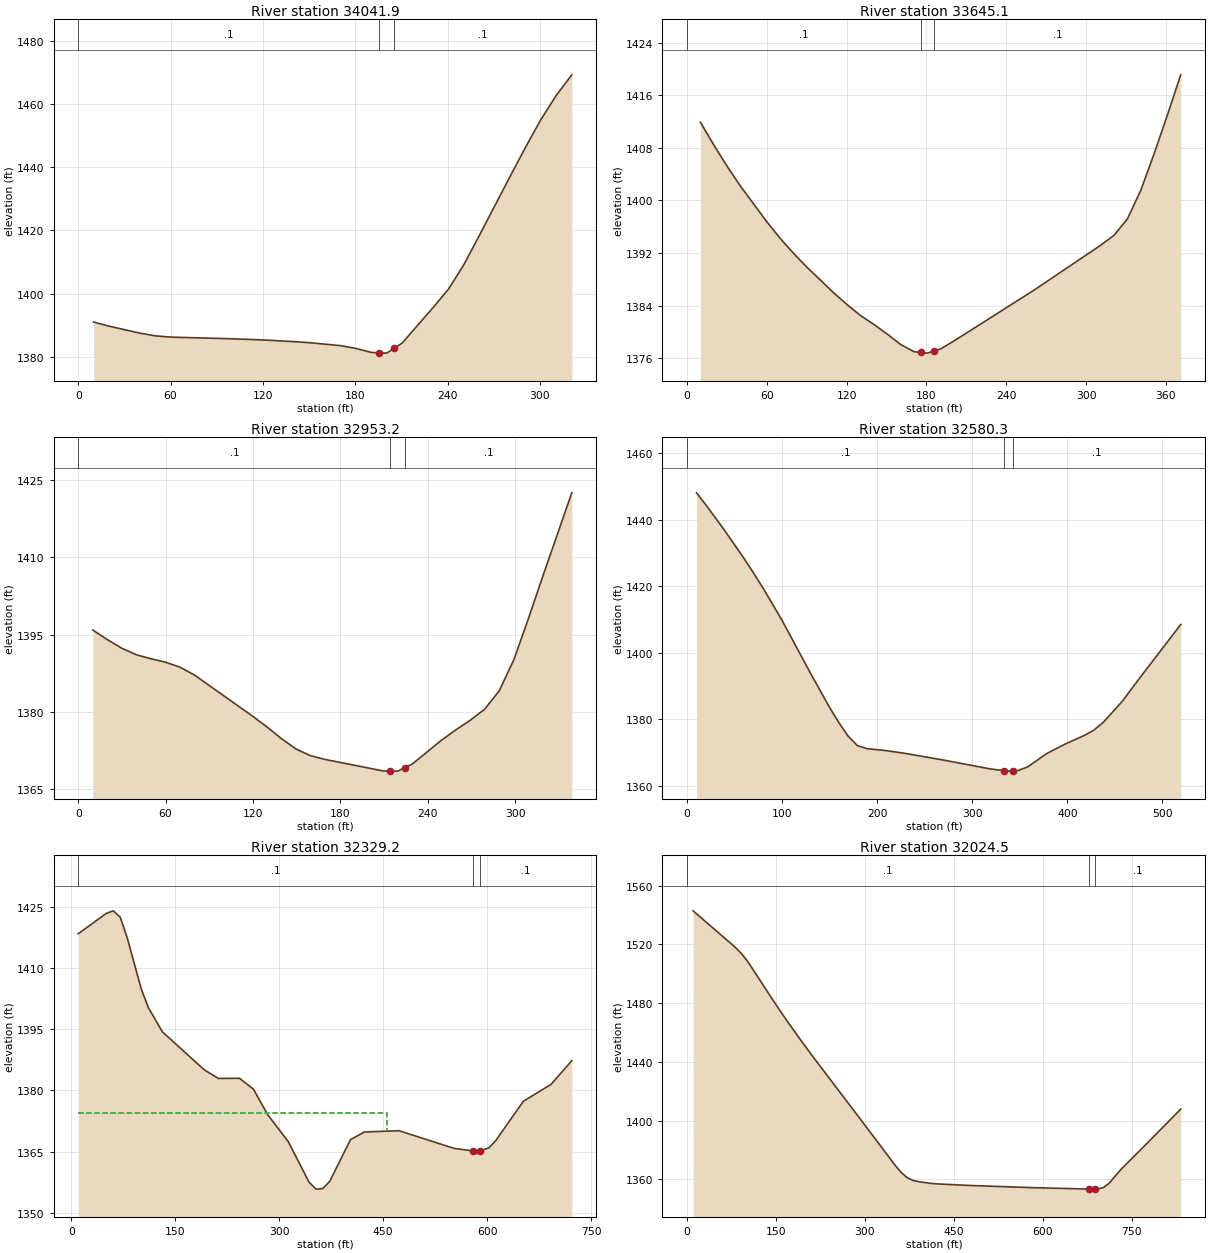
Type RM Length L Ch R = 1 ,34041.9 ,410.1,396.8,383.4
XS GIS Cut Line= 2
     1767469.454      144398.845     1767224.669       144605.97
#Sta/Elev= 25
      10 1391.06      20 1389.77    40.1 1387.55    50.1  1386.7    60.1  1386.3
   100.2 1385.77   120.2  1385.4   140.3 1384.87   150.3 1384.53   170.3 1383.62
   180.4 1382.72   190.4 1381.47   195.4 1381.35   200.4 1381.24   205.4 1382.81
   210.4 1384.38   230.5 1395.59   240.5 1401.41   250.5 1409.13   260.5  1418.3
   280.6 1437.07   290.6 1446.25   300.6 1455.02   310.6 1462.69   320.7 1469.18
#Mann= 3 , 0 , 0
       0      .1       0   195.4    .045       0   205.4      .1       0
Bank Sta=195.4,205.4
XS Rating Curve= 0 ,0
Exp/Cntr=0.3,0.1

Type RM Length L Ch R = 1 ,33645.1 ,696.2,691.9,687.3
XS GIS Cut Line= 2
     1767095.216      144071.681      1767015.19       144434.15
#Sta/Elev= 28
      10 1411.88    20.1 1408.42    30.1 1405.19    40.1 1402.18    60.2 1396.69
    70.2 1394.19    80.3 1391.91    90.3 1389.82   110.4 1385.94   120.4 1384.16
   130.4 1382.52   140.5 1381.16   150.5  1379.7   160.5 1378.13   170.6 1377.03
   175.6 1376.92   180.6 1376.81   185.6 1377.13   190.6 1377.44   200.6 1378.65
   260.8 1386.37     311  1393.2     321  1394.7   331.1  1397.2   341.1 1401.52
   351.1 1407.05   361.2 1412.99   371.2 1419.09
#Mann= 3 , 0 , 0
       0      .1       0   175.6    .045       0   185.6      .1       0
Bank Sta=175.6,185.6
XS Rating Curve= 0 ,0
Exp/Cntr=0.3,0.1

Type RM Length L Ch R = 1 ,32953.2 ,377.7,372.9,368.1
XS GIS Cut Line= 2
     1766389.107      144017.546     1766391.461      144356.479
#Sta/Elev= 28
      10 1395.92    19.9 1394.08    29.9 1392.39    39.9 1391.12    49.8 1390.35
    59.8 1389.69    69.8 1388.72    79.8 1387.19   119.6 1379.23   129.6 1377.11
   139.6 1374.83   149.5 1372.84   159.5 1371.53   169.5 1370.81   209.3 1368.58
   214.3 1368.56   219.3 1368.54   224.3 1369.22   229.3  1369.9   249.2 1374.49
   259.2 1376.54   269.2 1378.42   279.1 1380.56   289.1 1384.14   299.1 1390.16
     309 1398.04     319 1406.36   338.9 1422.54
#Mann= 3 , 0 , 0
       0      .1       0   214.3    .045       0   224.3      .1       0
Bank Sta=214.3,224.3
XS Rating Curve= 0 ,0
Exp/Cntr=0.3,0.1

Type RM Length L Ch R = 1 ,32580.3 ,272.3,251.1,230
XS GIS Cut Line= 3
      1765944.75      143947.267     1766065.289      144388.654
     1766107.655      144433.374
#Sta/Elev= 30
     9.9 1448.01    19.9 1444.33    39.8 1436.57    59.7 1428.38    69.6 1424.07
    79.6 1419.54    99.5 1409.91   129.3 1394.11   149.2 1383.92   159.1 1379.26
   169.1 1375.08     179 1372.18     189 1371.24   208.9 1370.66   228.8 1369.84
   268.6 1367.87   318.3 1365.18   333.2 1364.61   338.2 1364.49   343.2 1364.59
   348.1 1364.69   358.1 1365.73     378 1369.72   397.9 1372.65   417.8  1375.2
   427.7 1376.76   437.7 1379.12   457.5 1385.37   475.2 1392.12   519.2 1408.49
#Mann= 3 , 0 , 0
       0      .1       0   333.2    .045       0   343.2      .1       0
Bank Sta=333.2,343.2
XS Rating Curve= 0 ,0
Exp/Cntr=0.3,0.1

Type RM Length L Ch R = 1 ,32329.2 ,308,304.7,301.4
XS GIS Cut Line= 3
     1765369.481      144199.955     1765592.632      144374.265
     1766017.224      144485.932
#Sta/Elev= 30
    10.1 1418.39    50.6 1423.39    60.7 1424.02    70.8 1422.43    80.9 1417.35
   101.1 1404.84   111.2 1400.33   131.5 1394.35   192.1 1385.01   212.4 1382.92
   242.7 1382.96   262.9  1380.3   283.2 1374.09   313.1 1367.43     343 1357.52
     353 1355.78     363 1355.92     373 1357.69   402.9 1367.91   422.9 1369.79
   472.7 1370.11   552.6 1365.76  579.88 1365.15  584.67 1364.48   590.2  1365.2
   602.5 1365.89   612.4 1367.66   652.3 1377.32   692.3 1381.48   722.2 1387.28
#Mann= 3 , 0 , 0
    10.1      .1       0  579.88    .045       0   590.2      .1       0
#XS Ineff= 2 , 0
          455.03  1374.5
Permanent Ineff=
       F       F
Bank Sta=579.88,590.2
XS Rating Curve= 0 ,0
Exp/Cntr=0.3,0.1

Type RM Length L Ch R = 1 ,32024.5 ,602.4,608.3,614.2
XS GIS Cut Line= 2
     1765193.854      144673.073     1766024.285      144740.131
#Sta/Elev= 30
      10  1542.8    80.3 1518.31    90.3 1514.32   100.4  1509.3   110.4 1503.32
   140.5 1484.62   160.6 1472.54   170.6  1466.7   190.7 1455.34   210.8 1444.28
   281.1 1406.94   351.3 1369.41   361.4 1364.58   371.4 1361.08   381.4 1359.18
   391.5  1358.3   411.5 1357.19   421.6 1356.83   481.8 1355.69   582.2 1354.29
   677.6 1353.31   682.6 1353.27   687.6 1353.29   692.6  1353.3   702.6 1354.28
   712.7 1357.45   722.7 1362.29   732.8 1366.93   772.9 1383.12   833.1 1407.75
#Mann= 3 , 0 , 0
       0      .1       0   677.6    .045       0   687.6      .1       0
Bank Sta=677.6,687.6
XS Rating Curve= 0 ,0
Exp/Cntr=0.3,0.1

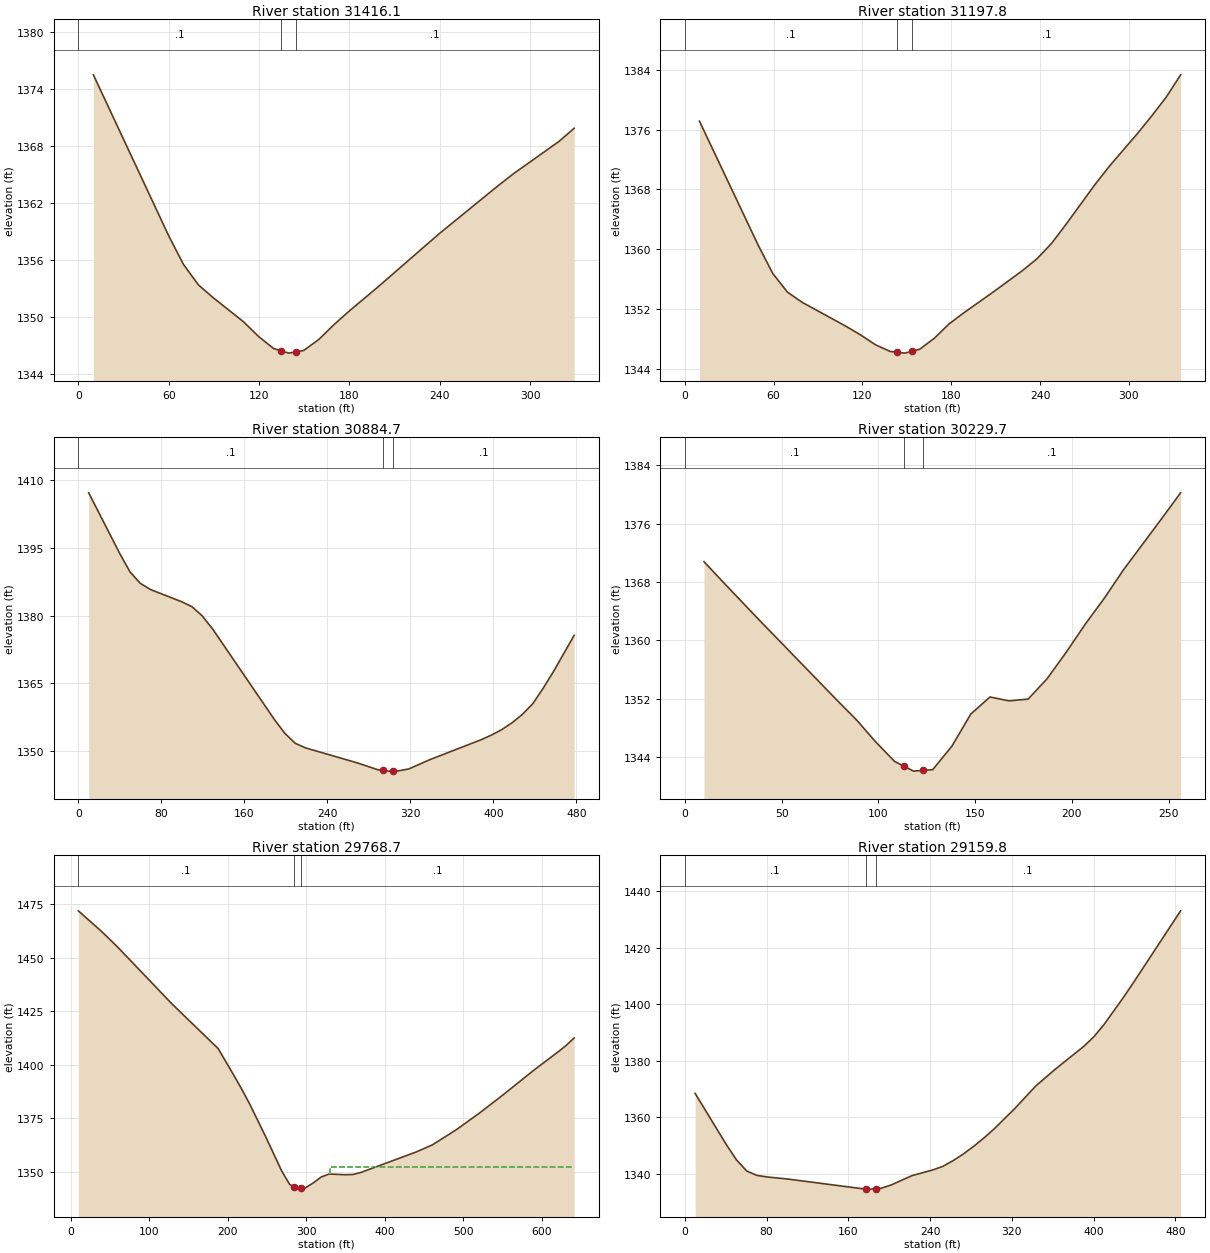
Type RM Length L Ch R = 1 ,31416.1 ,214.8,218.3,221.8
XS GIS Cut Line= 2
     1765595.912      145260.298     1765904.246      145375.629
#Sta/Elev= 21
      10 1375.48    59.9 1358.55    69.8  1355.5    79.8 1353.33    89.8 1351.96
   109.7 1349.45   119.7  1347.9   129.7 1346.63   134.7 1346.39   139.7 1346.15
   144.7 1346.29   149.6 1346.43   159.6 1347.58   169.6 1349.13   179.6 1350.55
   199.5  1353.2   239.4 1358.71   279.3 1363.87   289.3  1365.1   319.2 1368.47
   329.2 1369.85
#Mann= 3 , 0 , 0
       0      .1       0   134.7    .045       0   144.7      .1       0
Bank Sta=134.7,144.7
XS Rating Curve= 0 ,0
Exp/Cntr=0.3,0.1

Type RM Length L Ch R = 1 ,31197.8 ,309.3,313.1,316.9
XS GIS Cut Line= 3
     1765517.591      145432.228     1765746.549      145570.985
     1765786.561       145625.12
#Sta/Elev= 27
     9.9 1377.12    49.6 1360.51    59.5 1356.71    69.4 1354.23    79.3 1352.87
   109.1 1349.64     119 1348.48   128.9 1347.18   138.8 1346.29   143.7 1346.18
   148.7 1346.07   153.7 1346.33   158.7 1346.59   168.6 1348.06   178.5 1349.97
   188.4 1351.45   208.2 1354.22   228.1 1357.11     238 1358.71   247.9 1360.78
   257.8 1363.37   277.3 1368.68     287 1371.12   306.2 1375.55   315.8  1377.9
   325.4 1380.37     335 1383.32
#Mann= 3 , 0 , 0
       0      .1       0   143.7    .045       0   153.7      .1       0
Bank Sta=143.7,153.7
XS Rating Curve= 0 ,0
Exp/Cntr=0.3,0.1

Type RM Length L Ch R = 1 ,30884.7 ,655.6,655,654.3
XS GIS Cut Line= 2
     1765236.865      145531.496     1765598.266      145844.014
#Sta/Elev= 30
      10 1407.22    39.8 1393.82    49.8  1389.7    59.7 1387.16    69.7 1385.77
    99.5 1383.09   109.5 1381.98   119.4 1379.95   129.4 1377.05   189.1 1356.92
   199.1 1353.89     209 1351.71     219 1350.69   268.8 1347.37   288.7 1345.84
   293.6  1345.7   298.6 1345.54   303.6 1345.57   308.6  1345.6   318.5 1346.03
   338.4 1348.05   388.2  1352.5   398.2 1353.54   408.1 1354.75   418.1 1356.28
     428 1358.14     438  1360.5   447.9  1363.9   457.9 1367.62   477.8 1375.63
#Mann= 3 , 0 , 0
       0      .1       0   293.6    .045       0   303.6      .1       0
Bank Sta=293.6,303.6
XS Rating Curve= 0 ,0
Exp/Cntr=0.3,0.1

Type RM Length L Ch R = 1 ,30229.7 ,473.7,461.1,448.4
XS GIS Cut Line= 2
     1764870.974       145949.93     1765071.038      146109.982
#Sta/Elev= 28
     9.9 1370.79    19.7 1368.01    29.6 1365.25    39.4 1362.52    49.3 1359.82
    59.1 1357.13      69 1354.42    78.8 1351.74    88.7 1349.09    98.5  1346.1
   108.4 1343.38   113.2 1342.73   118.2 1342.05   123.2 1342.15   128.1 1342.25
     138 1345.47   147.8 1349.89   157.7 1352.22   167.5 1351.69   177.4 1351.93
   187.2 1354.72   197.1 1358.37   206.9  1362.2   216.8 1365.78   226.6 1369.64
   236.5 1373.16   246.4 1376.69   256.2 1380.23
#Mann= 3 , 0 , 0
       0      .1       0   113.2    .045       0   123.2      .1       0
Bank Sta=113.2,123.2
XS Rating Curve= 0 ,0
Exp/Cntr=0.3,0.1

Type RM Length L Ch R = 1 ,29768.7 ,597.4,608.8,620.2
XS GIS Cut Line= 4
     1764586.177      146286.509     1764720.337      146418.316
     1765002.781      146432.438      1765167.54      146477.158
#Sta/Elev= 30
     9.9 1471.81    39.6 1462.15    59.4 1455.13   128.7 1428.55   188.1 1407.49
   208.3 1394.87   218.4 1388.36   228.5 1381.45   248.7 1366.29   268.9 1350.46
     279 1344.19   284.1 1343.03   289.1 1341.91   294.1 1342.21   299.2 1342.52
   309.3 1344.83   319.4 1347.59   329.5 1348.96   349.7 1348.63   359.8 1348.74
   369.9 1349.69   440.6 1359.29   460.8 1362.54     491 1369.52   521.1 1377.45
   551.2 1385.96   591.4 1397.76   621.5 1406.07   631.5 1409.02   641.6 1412.47
#Mann= 3 , 0 , 0
     9.9      .1       0   284.1    .045       0   294.1      .1       0
#XS Ineff= 2 , 0
                          330.03          1352.4
Permanent Ineff=
       F       F
Bank Sta=284.1,294.1
XS Rating Curve= 0 ,0
Exp/Cntr=0.3,0.1

Type RM Length L Ch R = 1 ,29159.8 ,363.3,361.4,359.5
XS GIS Cut Line= 3
     1764449.663      146856.103     1764732.106       147051.46
     1764870.974      147079.704
#Sta/Elev= 30
    10.1 1368.42    40.4  1350.4    50.5 1344.89    60.6 1340.91    70.7 1339.34
    80.8 1338.79     101 1338.05   171.7 1334.73   176.8 1334.61   181.8 1334.49
   186.8 1334.63   191.9 1334.77     202 1335.97   222.2 1339.26   242.4 1341.26
   252.5 1342.56   262.6  1344.6   272.7 1346.98   282.8  1349.7   292.9 1352.69
     303 1355.94   323.2 1363.17   343.4 1371.05   362.3 1376.92   390.7 1385.17
   400.1 1388.43   409.6 1392.52   428.4 1402.02   437.9 1407.07   485.1 1433.08
#Mann= 3 , 0 , 0
       0      .1       0   176.8    .045       0   186.8      .1       0
Bank Sta=176.8,186.8
XS Rating Curve= 0 ,0
Exp/Cntr=0.3,0.1

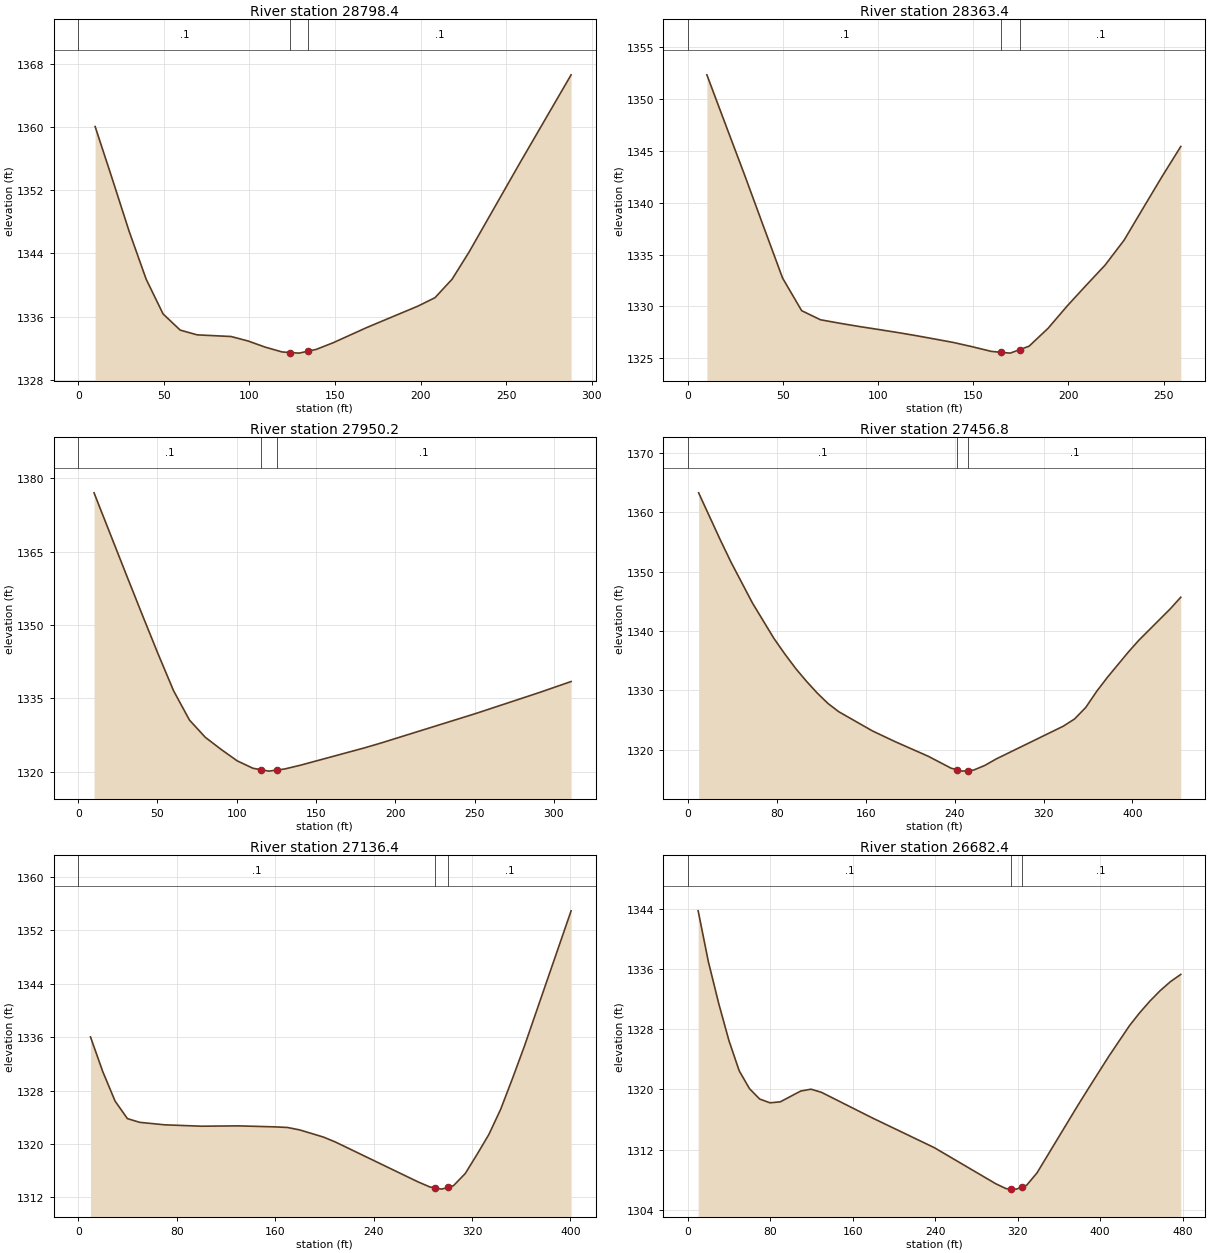
Type RM Length L Ch R = 1 ,28798.4 ,435.4,435,434.6
XS GIS Cut Line= 2
     1764254.306       147159.73     1764503.798      147303.305
#Sta/Elev= 23
     9.9 1360.04    19.9 1353.43    29.8 1346.77    39.7 1340.74    49.6 1336.34
    59.6  1334.3    69.5  1333.7    89.3 1333.49    99.3 1332.92   109.2 1332.15
   119.1 1331.54     124 1331.46     129 1331.39     134 1331.62     139 1331.86
   148.9  1332.7   168.7 1334.64   198.5 1337.34   208.4  1338.4   218.4 1340.74
   228.3 1344.17   258.1 1355.48   287.9 1366.58
#Mann= 3 , 0 , 0
       0      .1       0     124    .045       0     134      .1       0
Bank Sta=124,134
XS Rating Curve= 0 ,0
Exp/Cntr=0.3,0.1

Type RM Length L Ch R = 1 ,28363.4 ,412.2,413.2,414.3
XS GIS Cut Line= 2
      1764021.29      147517.491     1764249.598      147639.883
#Sta/Elev= 28
      10 1352.35    19.9 1347.51    29.9 1342.64    39.9 1337.64    49.8 1332.72
    59.8 1329.58    69.7  1328.7    79.7 1328.37    89.7 1328.06    99.6 1327.78
   109.6 1327.49   119.6 1327.18   129.5 1326.85   139.5 1326.51   149.4  1326.1
   159.4 1325.65   164.4 1325.56   169.4 1325.48   174.4 1325.82   179.3 1326.15
   189.3 1327.88   199.3 1330.03   209.2 1332.01   219.2 1333.97   229.2 1336.38
   239.1 1339.44   249.1 1342.51     259 1345.43
#Mann= 3 , 0 , 0
       0      .1       0   164.4    .045       0   174.4      .1       0
Bank Sta=164.4,174.4
XS Rating Curve= 0 ,0
Exp/Cntr=0.3,0.1

Type RM Length L Ch R = 1 ,27950.2 ,495.9,493.3,490.8
XS GIS Cut Line= 2
     1763745.908      147776.398     1764009.521      147941.156
#Sta/Elev= 20
      10 1377.05    30.1 1360.51    40.1 1352.36    50.1 1344.33    60.2 1336.54
    70.2 1330.56    80.2 1327.03    90.3 1324.53   100.3 1322.22   110.3  1320.7
   115.3 1320.41   120.3 1320.12   125.3 1320.34   130.4 1320.57   140.4 1321.35
   180.5 1324.87   190.5 1325.82   250.7  1331.9   290.8 1336.19   310.9 1338.45
#Mann= 3 , 0 , 0
       0      .1       0   115.3    .045       0   125.3      .1       0
Bank Sta=115.3,125.3
XS Rating Curve= 0 ,0
Exp/Cntr=0.3,0.1

Type RM Length L Ch R = 1 ,27456.8 ,324.2,320.4,316.7
XS GIS Cut Line= 4
     1763503.452      148124.521     1763567.002       148244.56
     1763778.084      148341.532     1763853.352      148337.948
#Sta/Elev= 30
     9.7  1363.3    29.1  1355.4    38.8 1351.62    58.2 1344.69    77.6  1338.7
    87.3 1336.11      97 1333.68   106.7 1331.52   116.4 1329.53   126.1 1327.77
   135.8 1326.38   166.1 1323.14   186.3 1321.35   216.6 1318.84   236.8 1316.86
   241.9 1316.61   246.9 1316.36   251.9 1316.44     257 1316.53   267.1 1317.31
   277.2 1318.39   337.8 1323.94   347.9 1325.15     358  1327.1   368.1 1329.88
   377.5 1332.18   396.4 1336.46   405.8 1338.44     434 1343.72   443.5 1345.69
#Mann= 3 , 0 , 0
       0      .1       0   241.9    .045       0   251.9      .1       0
Bank Sta=241.9,251.9
XS Rating Curve= 0 ,0
Exp/Cntr=0.3,0.1

Type RM Length L Ch R = 1 ,27136.4 ,446.3,454,461.8
XS GIS Cut Line= 4
     1763312.828      148444.847     1763446.542      148565.547
     1763623.515      148609.606     1763656.467      148628.435
#Sta/Elev= 26
      10 1336.03      20 1330.82      30 1326.41      40 1323.79      50 1323.23
    70.1 1322.86   100.1 1322.65   130.1  1322.7   160.1 1322.55   170.1 1322.46
   180.1 1322.09   199.3 1321.02   208.9 1320.29   276.1 1314.31   285.7 1313.55
   290.3 1313.39   295.3 1313.22   300.3 1313.48   304.9 1313.73   314.5 1315.56
   324.1 1318.43   333.7 1321.42   343.3  1325.2   352.9 1329.82   362.5 1334.62
   400.5 1354.93
#Mann= 3 , 0 , 0
       0      .1       0   290.3    .045       0   300.3      .1       0
Bank Sta=290.3,300.3
XS Rating Curve= 0 ,0
Exp/Cntr=0.3,0.1

Type RM Length L Ch R = 1 ,26682.4 ,463.1,472.8,482.6
XS GIS Cut Line= 2
     1763041.524      148769.848     1763426.829      149053.002
#Sta/Elev= 30
      10 1343.74    19.9 1336.99    29.9 1331.46    39.8 1326.53    49.8 1322.49
    59.8 1320.11    69.7 1318.73    79.7 1318.23    89.7 1318.36   109.6  1319.8
   119.5 1320.04   129.5 1319.63   179.3  1316.2   239.1 1312.27   298.8 1307.47
   308.8 1306.82   313.8 1306.79   318.8 1306.76   323.8 1307.02   328.7 1307.28
   338.7 1308.91   378.5 1317.92   388.5 1320.11   408.4 1324.41   428.4 1328.47
   438.3 1330.19   448.3 1331.75   458.2 1333.13   468.2 1334.33   478.2 1335.29
#Mann= 3 , 0 , 0
       0      .1       0   313.8    .045       0   323.8      .1       0
Bank Sta=313.8,323.8
XS Rating Curve= 0 ,0
Exp/Cntr=0.3,0.1

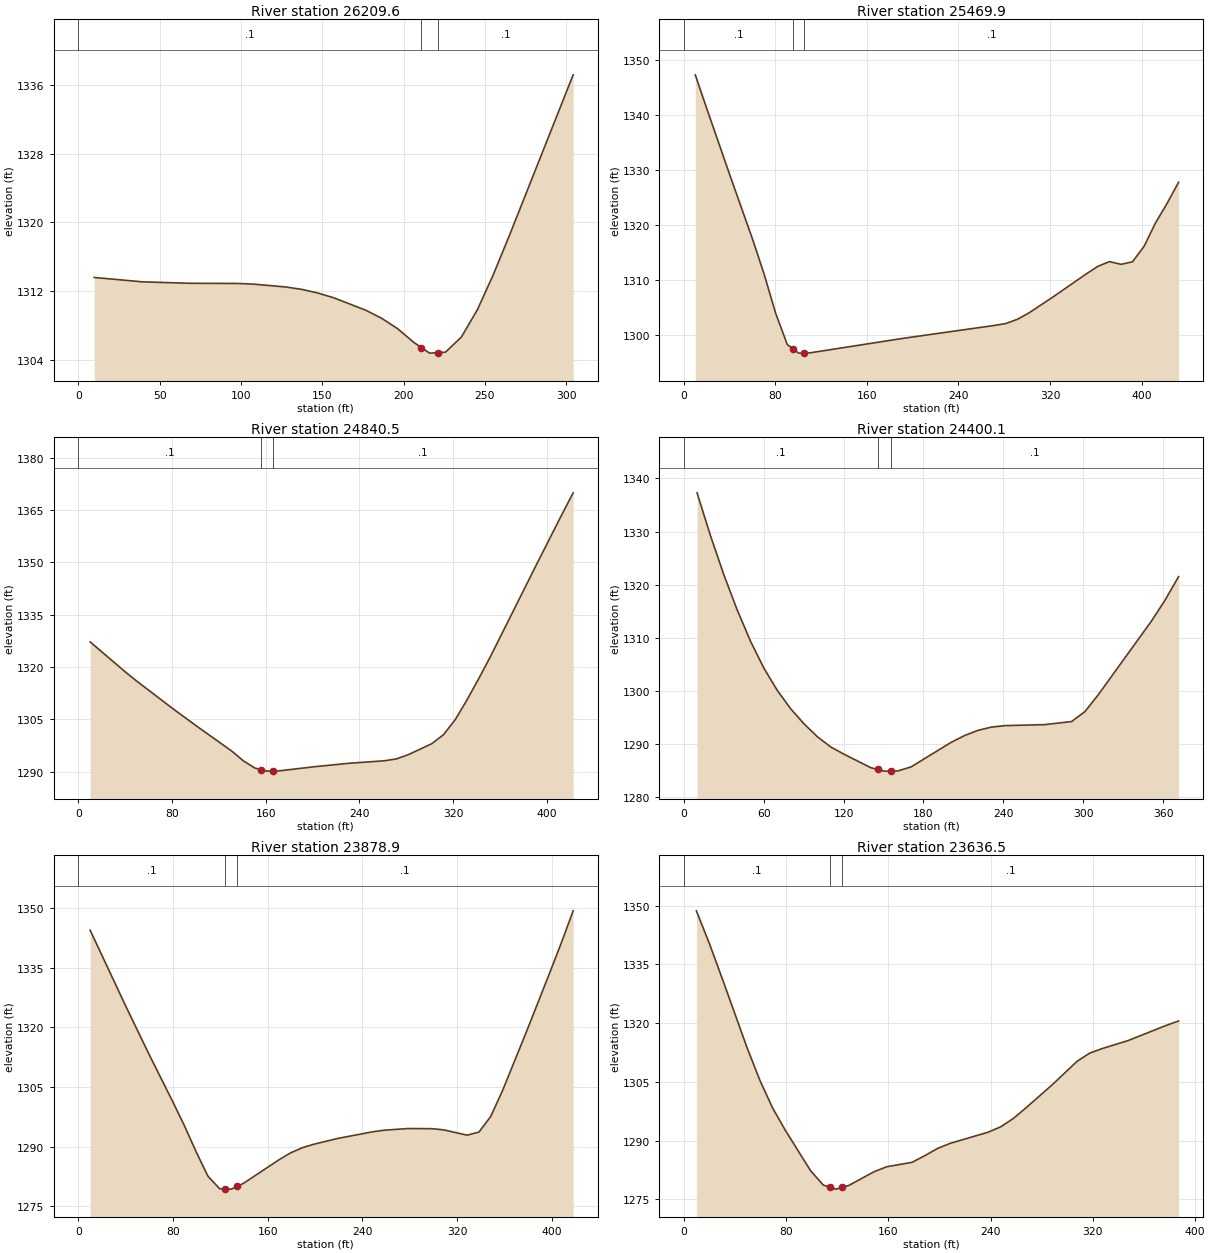
Type RM Length L Ch R = 1 ,26209.6 ,747.2,739.7,732.2
XS GIS Cut Line= 2
     1762860.918      149085.052     1762995.079      149358.081
#Sta/Elev= 22
     9.8 1313.58    39.3 1313.07    68.7  1312.9    98.1 1312.88   107.9  1312.8
   127.6 1312.47   137.4 1312.19   147.2 1311.77     157 1311.21   176.6 1309.77
   186.5 1308.82   196.3 1307.61   206.1 1306.03   210.9 1305.41   215.9 1304.76
   220.9 1304.81   225.7 1304.87   235.5 1306.64   245.3 1309.81   255.1  1313.9
     265 1318.47   304.2  1337.2
#Mann= 3 , 0 , 0
       0      .1       0   210.9    .045       0   220.9      .1       0
Bank Sta=210.9,220.9
XS Rating Curve= 0 ,0
Exp/Cntr=0.3,0.1

Type RM Length L Ch R = 1 ,25469.9 ,634,629.4,624.7
XS GIS Cut Line= 2
     1762170.557      149388.127     1762489.034      149680.537
#Sta/Elev= 26
    10.1 1347.27    20.1 1341.16    40.2 1329.09    60.3 1317.27    70.4 1310.91
    80.4 1303.83    90.5 1298.19    95.5  1297.4   100.5 1296.62   105.5 1296.65
   110.6 1296.68     191 1299.29   271.5 1301.66   281.5 1302.01   291.6 1302.78
   301.6 1303.93   321.8 1306.72   351.9 1311.06     362 1312.43     372 1313.28
   382.1 1312.78   392.1 1313.24   402.2 1316.04   412.2 1320.31   422.3 1323.85
   432.4 1327.72
#Mann= 3 , 0 , 0
       0      .1       0    95.5    .045       0   105.5      .1       0
Bank Sta=95.5,105.5
XS Rating Curve= 0 ,0
Exp/Cntr=0.3,0.1

Type RM Length L Ch R = 1 ,24840.5 ,443.9,440.4,436.9
XS GIS Cut Line= 2
     1761771.157      149897.077     1762140.687      150101.849
#Sta/Elev= 26
    10.1  1327.2    40.2 1318.56    50.3 1315.83    80.5  1308.1   100.6 1303.14
   130.8 1295.92   140.8  1293.1   150.9 1290.97   155.9 1290.54   160.9 1290.11
   165.9 1290.14     171 1290.17   201.2 1291.36   231.4 1292.37   261.5 1293.08
   271.6 1293.62   281.6 1294.81   301.8 1297.98   311.8 1300.56   321.9 1304.91
   331.9 1310.58     342 1316.72   352.1 1323.13   392.3 1350.11   412.4 1363.43
   422.5 1369.96
#Mann= 3 , 0 , 0
       0      .1       0   155.9    .045       0   165.9      .1       0
Bank Sta=155.9,165.9
XS Rating Curve= 0 ,0
Exp/Cntr=0.3,0.1

Type RM Length L Ch R = 1 ,24400.1 ,524,521.3,518.6
XS GIS Cut Line= 2
     1761540.852      150288.889     1761888.075      150421.057
#Sta/Elev= 30
      10  1337.3    20.1 1329.24    30.1  1321.9    40.2 1315.24    50.2 1309.35
    60.2 1304.31    70.3 1300.11    80.3 1296.67    90.4 1293.82   100.4  1291.4
   110.5 1289.47   120.5  1288.1   140.6 1285.57   145.6 1285.26   150.6 1284.94
   155.6 1284.95   160.7 1284.97   170.7 1285.74   200.8 1290.36   210.9 1291.64
   220.9 1292.61   230.9 1293.22     241  1293.5   271.1 1293.69   291.2 1294.27
   301.2 1296.14   311.3 1299.34   351.4 1313.27   361.5 1317.18   371.5 1321.53
#Mann= 3 , 0 , 0
       0      .1       0   145.6    .045       0   155.6      .1       0
Bank Sta=145.6,155.6
XS Rating Curve= 0 ,0
Exp/Cntr=0.3,0.1

Type RM Length L Ch R = 1 ,23878.9 ,239.4,242.4,245.3
XS GIS Cut Line= 2
      1761396.92      150782.067     1761806.463        150866.8
#Sta/Elev= 30
      10 1344.47    39.8 1325.56    59.7  1313.3    79.7 1301.42    89.6 1295.34
    99.6 1288.73   109.5 1282.63   119.5 1279.42   124.4 1279.38   129.4 1279.34
   134.4 1280.05   139.4 1280.76   169.3 1286.66   179.2 1288.43   189.2 1289.74
   199.2 1290.64   219.1 1292.08   248.9 1293.77   258.9 1294.17   278.8 1294.58
   298.7 1294.54   308.7 1294.25   328.6 1292.91   338.6 1293.69   348.5  1297.6
   358.5 1304.11   378.4 1318.69   398.3 1333.68   408.3 1341.35   418.2 1349.33
#Mann= 3 , 0 , 0
       0      .1       0   124.4    .045       0   134.4      .1       0
Bank Sta=124.4,134.4
XS Rating Curve= 0 ,0
Exp/Cntr=0.3,0.1

Type RM Length L Ch R = 1 ,23636.5 ,370.8,381.9,393
XS GIS Cut Line= 2
     1761323.955      150989.192     1761688.778      151118.645
#Sta/Elev= 30
     9.9 1348.66    19.9 1340.47    29.8 1331.67    49.6 1313.69    59.6 1305.39
    69.5 1298.35    79.4 1292.69    99.3 1282.29   109.2 1278.65   114.1 1278.14
   119.1 1277.62   124.1 1278.08     129 1278.54   148.9 1282.06   158.8 1283.33
   178.7 1284.47   188.6 1286.16   198.5    1288   208.4  1289.3   238.2 1292.16
   248.1 1293.55   258.1 1295.72     268 1298.45   287.9 1304.15   307.7 1310.25
   317.6 1312.34   327.6 1313.53   347.4 1315.52   377.2 1319.38   387.1 1320.54
#Mann= 3 , 0 , 0
       0      .1       0   114.1    .045       0   124.1      .1       0
Bank Sta=114.1,124.1
XS Rating Curve= 0 ,0
Exp/Cntr=0.3,0.1