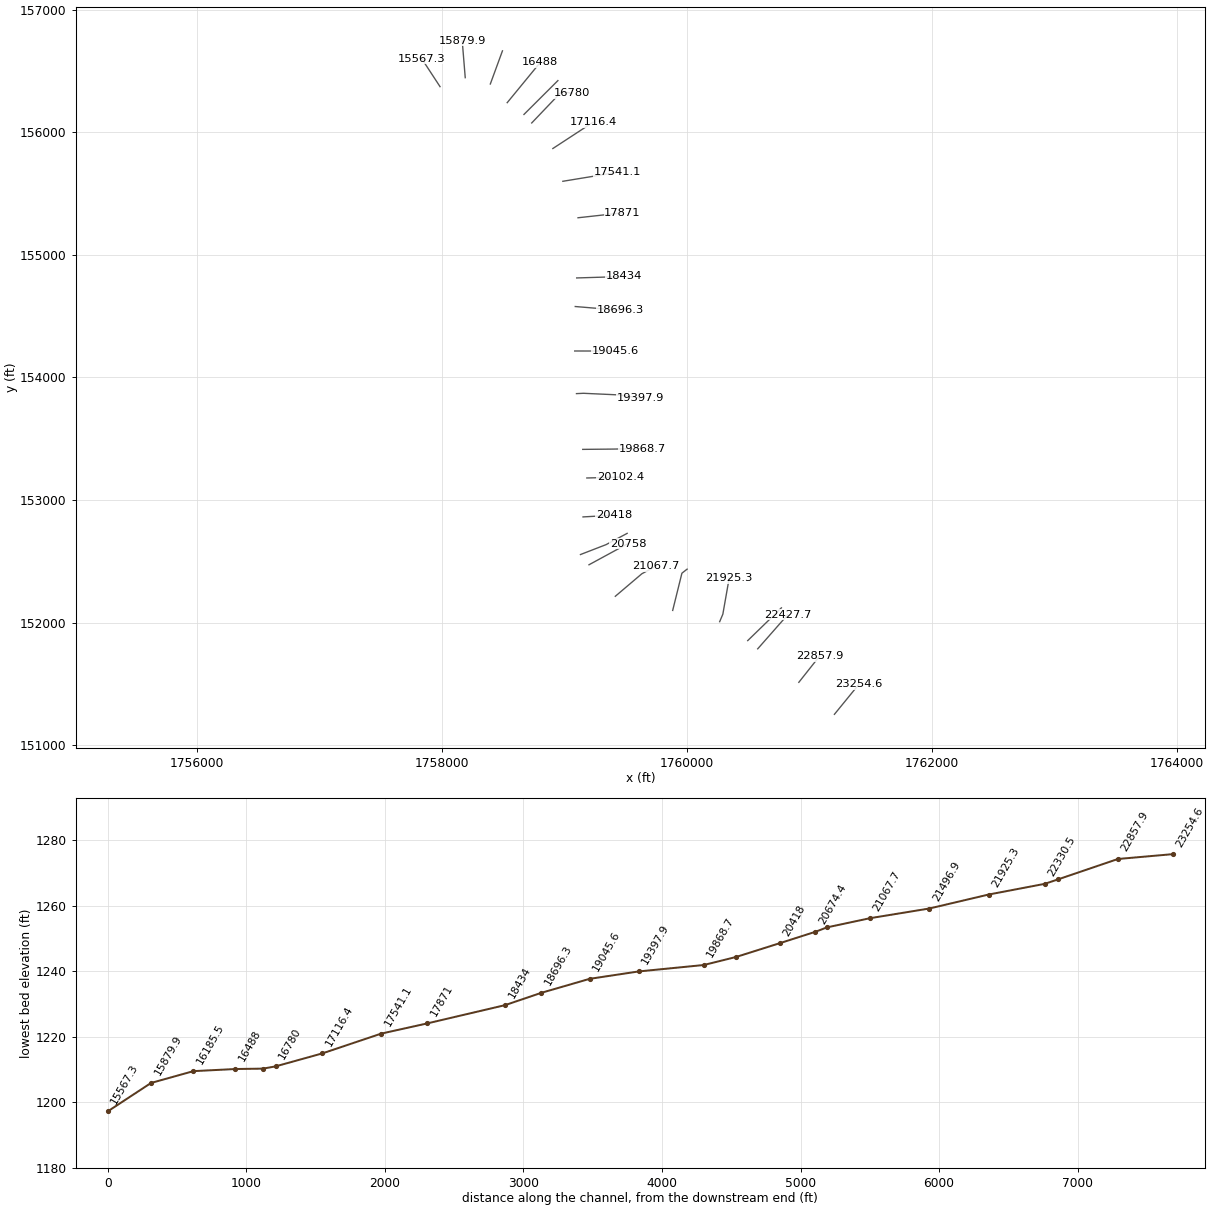
HEC-RAS study Clear Fork A.prj: Clear Fork A

--- Clear Fork A.g01 (geometry) --- (continued)

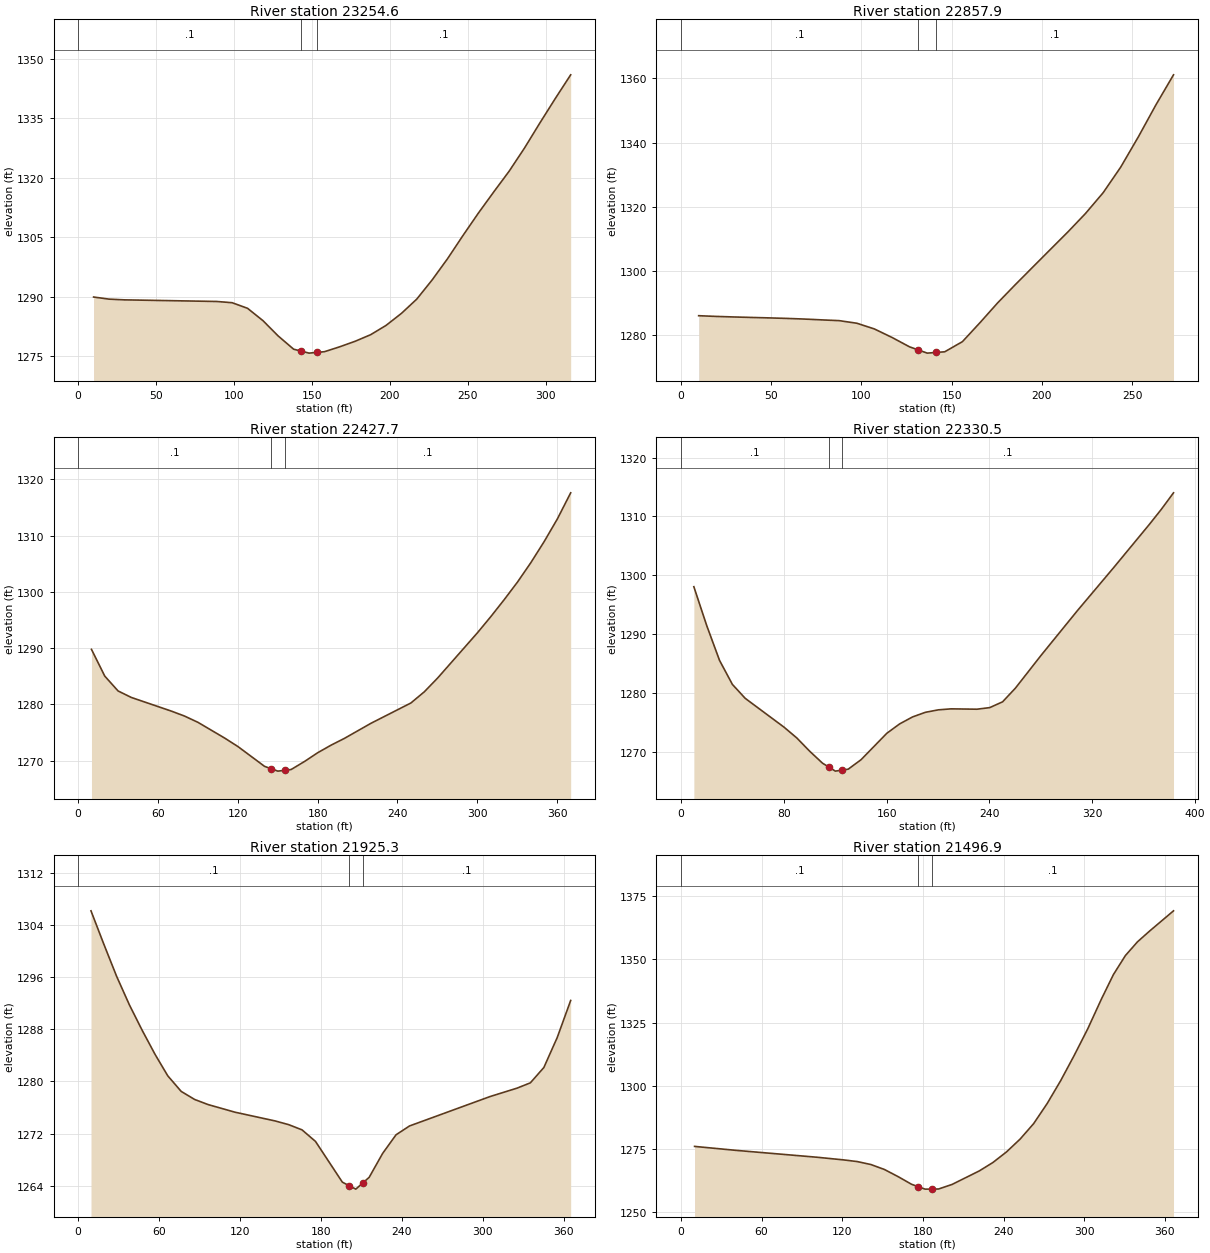
Type RM Length L Ch R = 1 ,23254.6 ,396.5,396.7,396.9
XS GIS Cut Line= 2
     1761201.563      151252.806     1761401.627       151497.59
#Sta/Elev= 29
     9.9 1289.92    19.8 1289.39    29.6 1289.21    88.9  1288.8    98.8 1288.49
   108.7 1287.08   118.6 1283.97   128.4  1280.1   138.3 1276.78   143.2 1276.29
   148.2 1275.79   153.2 1275.97   158.1 1276.15   167.9 1277.39   177.8 1278.78
   187.7 1280.43   197.6 1282.77   207.5 1285.81   217.3 1289.39   227.2 1294.23
   237.1 1299.59     247 1305.43   256.9 1311.08   266.7 1316.38   276.6 1321.61
   286.5 1327.47   296.4 1333.81   306.3 1339.97   316.1 1345.89
#Mann= 3 , 0 , 0
       0      .1       0   143.2    .045       0   153.2      .1       0
Bank Sta=143.2,153.2
XS Rating Curve= 0 ,0
Exp/Cntr=0.3,0.1

Type RM Length L Ch R = 1 ,22857.9 ,431.7,430.2,428.7
XS GIS Cut Line= 3
     1760911.021      151513.828     1760995.833      151620.782
     1761080.645      151727.736
#Sta/Elev= 30
     9.8 1285.98    19.5 1285.76    29.2 1285.59      39 1285.44    48.7  1285.3
    58.5 1285.14    68.2 1284.94      78 1284.68    87.7 1284.44    97.5 1283.63
   107.2 1281.85     117 1279.19   126.7 1276.27   131.5 1275.31   136.5 1274.31
   141.5 1274.53   146.2 1274.73     156 1277.89   165.7 1283.79   175.5 1289.97
   185.2  1295.6     195 1301.14   204.7 1306.62   214.5 1312.13   224.2 1317.85
     234 1324.34   243.7 1332.29   253.5 1341.75   263.2 1351.69     273 1361.11
#Mann= 3 , 0 , 0
       0      .1       0   131.5    .045       0   141.5      .1       0
Bank Sta=131.5,141.5
XS Rating Curve= 0 ,0
Exp/Cntr=0.3,0.1

Type RM Length L Ch R = 1 ,22427.7 ,98.4,97.2,95.9
XS GIS Cut Line= 2
      1760575.48      151787.095     1760820.264      152064.831
#Sta/Elev= 30
      10 1289.77      20 1285.01      30 1282.37      40 1281.21      70 1278.79
      80  1277.9    90.1 1276.78   110.1 1273.99   120.1 1272.48   140.1 1268.96
   145.1 1268.53   150.1 1268.11   155.1 1268.25   160.1  1268.4   170.1 1269.82
   180.1 1271.39   190.1 1272.73   200.1 1273.93   220.1 1276.62   250.1 1280.23
   260.1  1282.2   270.2 1284.67   300.2 1292.74   310.2  1295.6   320.2  1298.6
   330.2 1301.73   340.2 1305.17   350.2 1308.91   360.2 1312.97   370.2 1317.61
#Mann= 3 , 0 , 0
       0      .1       0   145.1    .045       0   155.1      .1       0
Bank Sta=145.1,155.1
XS Rating Curve= 0 ,0
Exp/Cntr=0.3,0.1

Type RM Length L Ch R = 1 ,22330.5 ,390.8,405.2,419.3
XS GIS Cut Line= 3
     1760493.812      151853.985      1760695.04       152048.99
     1760768.568      152121.079
#Sta/Elev= 30
      10 1298.05      20 1291.46      30 1285.53      40 1281.45      50 1279.08
    80.1  1274.2    90.1 1272.36   100.1 1270.11   110.1 1268.07   115.1  1267.4
   120.1 1266.72   125.1 1266.89   130.1 1267.05   140.1 1268.66   160.1 1273.14
   170.1 1274.74   180.1 1275.92   190.1 1276.71   200.2 1277.13   210.2  1277.3
   230.2 1277.24   240.2 1277.51   250.2 1278.49   260.2 1280.82   280.2  1286.4
   308.3 1293.95   336.4 1301.23   364.5 1308.66   373.8 1311.22   383.2    1314
#Mann= 3 , 0 , 0
       0      .1       0   115.1    .045       0   125.1      .1       0
Bank Sta=115.1,125.1
XS Rating Curve= 0 ,0
Exp/Cntr=0.3,0.1

Type RM Length L Ch R = 1 ,21925.3 ,430.2,428.4,426.7
XS GIS Cut Line= 3
     1760264.792      152008.342     1760290.683      152069.538
     1760342.464       152363.75
#Sta/Elev= 29
     9.5 1306.23      19 1301.12    28.5 1296.17      38 1291.77    47.5 1287.85
      57 1284.17    66.4 1280.88    76.4 1278.47    86.4 1277.23    96.3 1276.45
   116.2 1275.28   146.1 1273.93   156.1 1273.36     166 1272.56     176 1270.78
   195.9 1264.52   200.9 1263.98   205.9 1263.45   210.9 1264.37   215.8 1265.27
   225.8 1268.95   235.7  1271.8   245.7 1273.16   305.4 1277.68   325.4 1278.97
   335.3 1279.79   345.3 1282.14   355.2 1286.74   365.2 1292.45
#Mann= 3 , 0 , 0
       0      .1       0   200.9    .045       0   210.9      .1       0
Bank Sta=200.9,210.9
XS Rating Curve= 0 ,0
Exp/Cntr=0.3,0.1

Type RM Length L Ch R = 1 ,21496.9 ,442.3,429.2,416.2
XS GIS Cut Line= 3
      1759881.14      152100.136     1759956.458      152403.763
     1759998.825      152436.714
#Sta/Elev= 29
    10.1 1276.07    40.4 1274.53   100.9  1271.8   121.1 1270.73   131.2 1270.07
   141.3 1268.91   151.4 1266.94   161.5 1264.14   171.6 1261.09   176.6 1260.14
   181.6 1259.18   186.6  1259.2   191.7 1259.23   201.8 1261.05     222 1266.39
   232.1  1269.7   242.2 1273.88   252.3 1278.93   262.4 1285.06   272.5 1293.03
   282.6 1302.12   292.6 1312.03   302.7 1322.57   312.8 1334.25   321.8 1344.01
   330.7 1351.51   339.7 1356.95   348.6 1361.15   366.5  1369.2
#Mann= 3 , 0 , 0
       0      .1       0   176.6    .045       0   186.6      .1       0
Bank Sta=176.6,186.6
XS Rating Curve= 0 ,0
Exp/Cntr=0.3,0.1

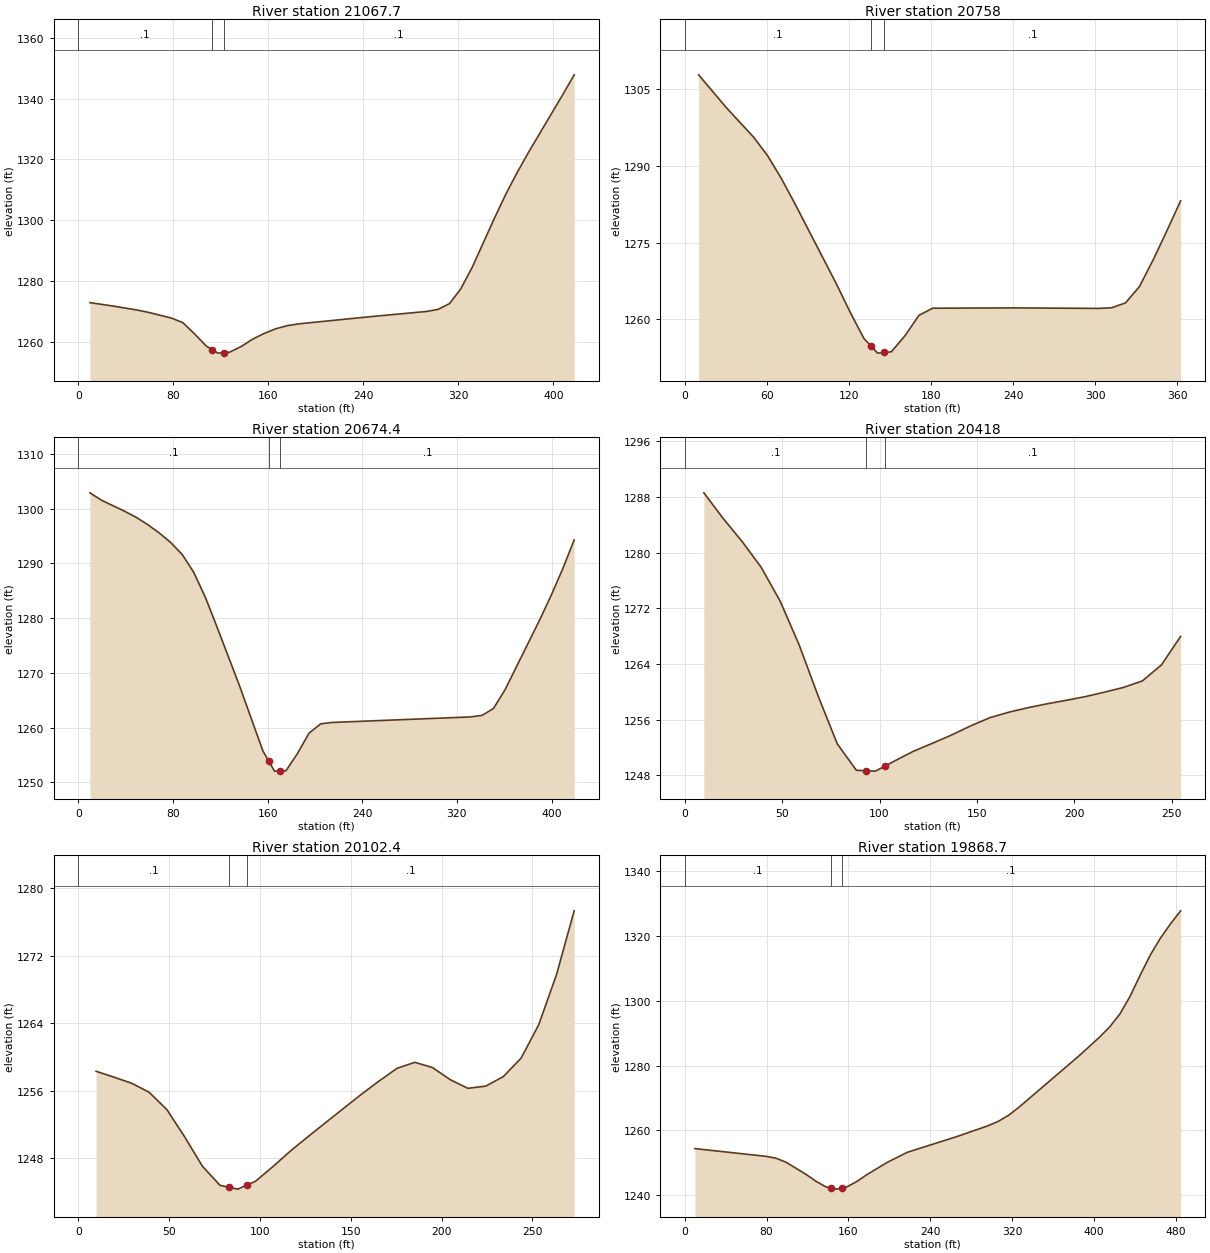
Type RM Length L Ch R = 1 ,21067.7 ,313.5,309.7,305.9
XS GIS Cut Line= 3
     1759412.755      152215.467     1759629.295      152399.055
     1759746.979      152462.605
#Sta/Elev= 30
     9.8 1272.82    29.4  1271.7    48.9 1270.43    58.7 1269.66    78.3 1267.77
    88.1 1266.22    97.9 1262.54   107.7 1258.55   112.5  1257.4   117.5 1256.21
   122.5 1256.36   127.3  1256.5   137.1 1258.38   146.8  1260.8   156.6  1262.7
   166.4 1264.24   176.2 1265.27     186 1265.86   244.7 1268.16   293.4 1269.93
     303 1270.61   312.6  1272.5   322.1 1277.35   331.7 1284.43   350.8  1300.9
   360.3 1308.71   369.9 1315.86   379.4 1322.46   408.1 1341.34   417.6  1347.8
#Mann= 3 , 0 , 0
       0      .1       0   112.5    .045       0   122.5      .1       0
Bank Sta=112.5,122.5
XS Rating Curve= 0 ,0
Exp/Cntr=0.3,0.1

Type RM Length L Ch R = 1 ,20758   ,86.2,83.6,81
XS GIS Cut Line= 2
     1759197.751       152472.46     1759516.293      152645.414
#Sta/Elev= 24
    10.1  1307.8    30.2 1301.44    50.3 1295.62    60.4 1292.05    70.5 1287.59
    80.5 1282.62   110.8 1266.96   120.8 1261.46   130.9  1256.3     136 1254.84
     141 1253.41     146 1253.54     151 1253.67   161.1 1256.85   171.2  1260.8
   181.2 1262.19   241.6 1262.25   302.1 1262.15   312.1 1262.27   322.2 1263.23
   332.3 1266.38   342.3 1271.57   352.4 1277.28   362.5 1283.18
#Mann= 3 , 0 , 0
       0      .1       0     136    .045       0     146      .1       0
Bank Sta=136,146
XS Rating Curve= 0 ,0
Exp/Cntr=0.3,0.1

Type RM Length L Ch R = 1 ,20674.4 ,262.7,256.4,250.1
XS GIS Cut Line= 3
     1759128.218      152555.914     1759337.436      152636.779
     1759509.256      152728.573
#Sta/Elev= 29
     9.8 1302.89    19.5 1301.55      39 1299.54    48.8 1298.43    58.5 1297.11
    68.3 1295.58      78 1293.83    87.8 1291.63    97.5 1288.39   107.3 1283.85
     117 1278.51   136.5  1267.5     156 1255.75   160.8 1253.95   165.8 1252.06
   170.8 1252.09   175.5 1252.12   185.3  1255.3     195 1258.99   204.8 1260.69
   214.5 1260.95   331.4 1261.96   341.2 1262.24   350.9  1263.5   360.7 1266.94
   389.9 1279.65   399.6 1284.13   409.4 1288.98   419.1 1294.28
#Mann= 3 , 0 , 0
       0      .1       0   160.8    .045       0   170.8      .1       0
Bank Sta=160.8,170.8
XS Rating Curve= 0 ,0
Exp/Cntr=0.3,0.1

Type RM Length L Ch R = 1 ,20418   ,316.3,315.6,314.9
XS GIS Cut Line= 2
     1759149.141      152862.733      1759403.34      152876.855
#Sta/Elev= 28
     9.8 1288.61    19.6 1284.96    29.4 1281.62    39.2 1277.91      49 1273.02
    58.8 1266.69    68.5 1259.37    78.3 1252.51    88.1 1248.71    92.9 1248.65
    97.9 1248.59   102.9 1249.33   107.7 1250.05   117.5 1251.46   127.3 1252.61
   137.1  1253.8   146.9 1255.11   156.7 1256.28   166.5 1257.07   176.3 1257.72
     186 1258.27   195.8 1258.77   205.6  1259.3   215.4 1259.94   225.2 1260.62
     235 1261.57   244.8 1263.88   254.6 1267.96
#Mann= 3 , 0 , 0
       0      .1       0    92.9    .045       0   102.9      .1       0
Bank Sta=92.9,102.9
XS Rating Curve= 0 ,0
Exp/Cntr=0.3,0.1

Type RM Length L Ch R = 1 ,20102.4 ,234,233.7,233.4
XS GIS Cut Line= 3
      1759180.18       153180.21     1759316.637      153183.664
     1759453.093      153187.119
#Sta/Elev= 30
     9.8 1258.32    19.5 1257.63    29.3 1256.91      39 1255.83    48.8 1253.77
    58.5 1250.57    68.3 1247.09      78 1244.82    82.8  1244.6    87.8 1244.37
    92.8 1244.85    97.5 1245.29   107.2 1247.05     117 1248.92   126.7 1250.62
   136.5  1252.3   146.3 1253.97     156 1255.62   165.8  1257.2   175.5 1258.67
   185.3 1259.38     195 1258.76   204.8 1257.32   214.5  1256.3   224.3 1256.56
     234 1257.69   243.8 1259.88   253.5 1263.83   263.3 1269.77     273 1277.31
#Mann= 3 , 0 , 0
       0      .1       0    82.8    .045       0    92.8      .1       0
Bank Sta=82.8,92.8
XS Rating Curve= 0 ,0
Exp/Cntr=0.3,0.1

Type RM Length L Ch R = 1 ,19868.7 ,472,470.8,469.6
XS GIS Cut Line= 3
     1759146.787      153413.498     1759393.925      153415.852
     1759631.648      153420.559
#Sta/Elev= 30
     9.9  1254.4    79.1 1252.03      89 1251.46    98.9 1250.23   118.6 1246.46
   128.5 1244.29   138.4 1242.54   143.3 1242.23   148.3 1241.91   153.3 1242.23
   158.2 1242.54   168.1 1244.24   177.9 1246.33   197.7 1250.11   217.5 1253.25
     267 1258.21   296.7 1261.47   306.6 1262.81   316.5 1264.65   326.4 1267.05
   385.8 1283.07   405.7 1288.79   415.6 1291.96   425.5  1295.9   435.4 1301.31
   445.3 1307.84   455.2 1314.05   465.1 1319.27     475  1323.7   484.9 1327.71
#Mann= 3 , 0 , 0
       0      .1       0   143.3    .045       0   153.3      .1       0
Bank Sta=143.3,153.3
XS Rating Curve= 0 ,0
Exp/Cntr=0.3,0.1

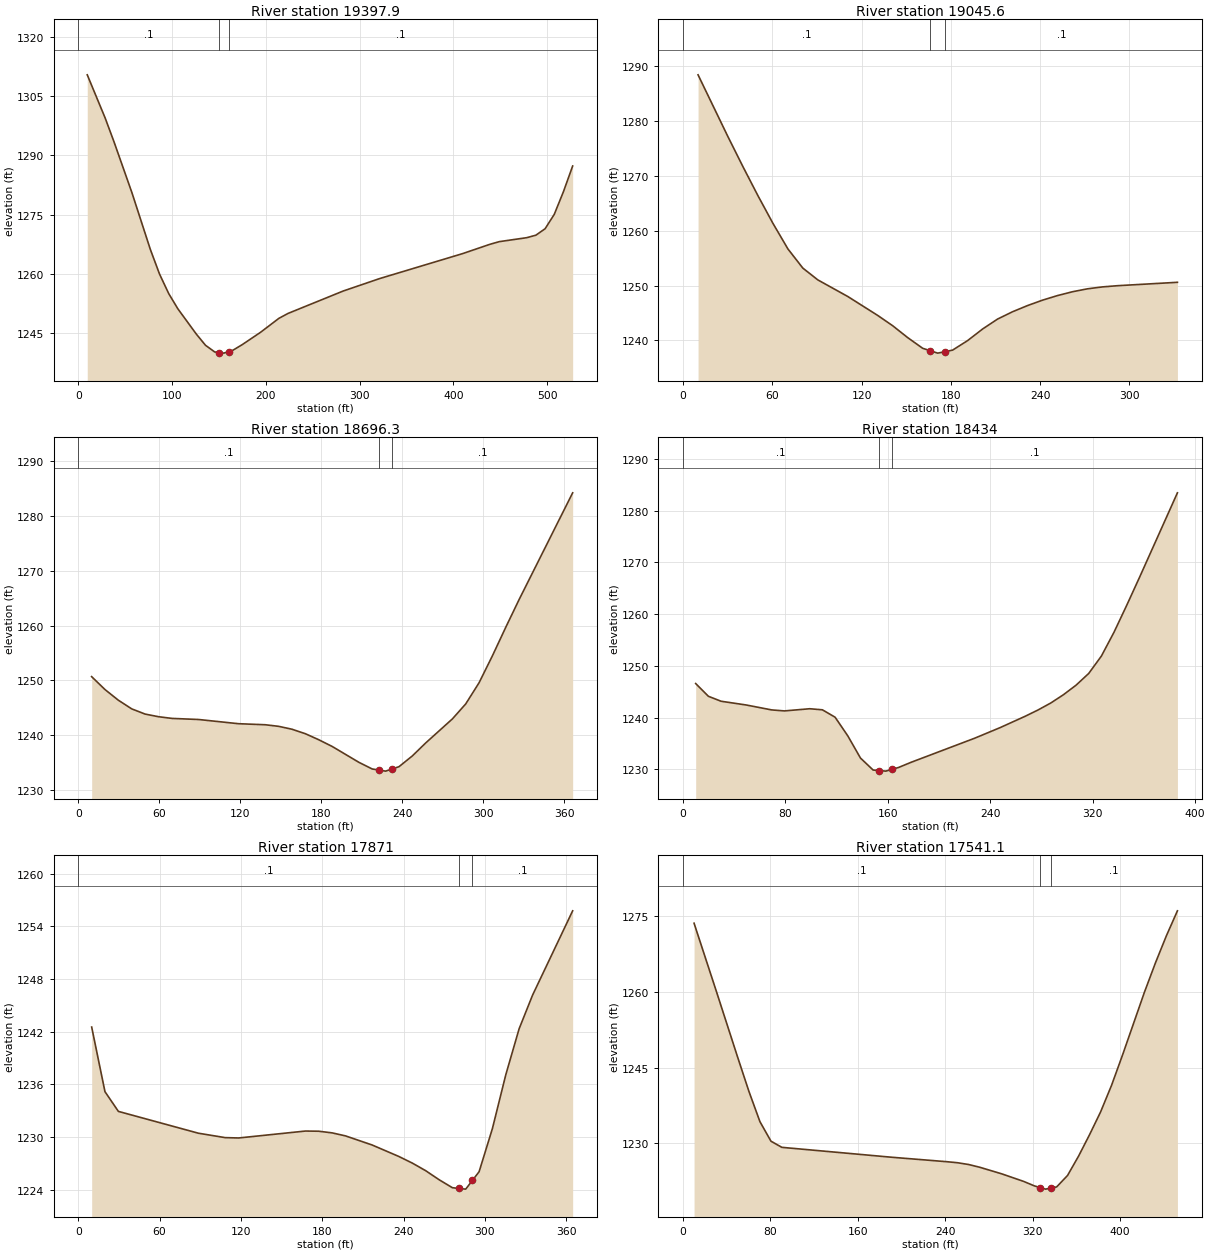
Type RM Length L Ch R = 1 ,19397.9 ,351.3,352.3,353.2
XS GIS Cut Line= 4
     1759095.573      153868.236      1759152.86      153870.878
     1759446.318      153857.437     1759620.447      153830.577
#Sta/Elev= 30
     9.6 1310.42    28.7 1299.48    38.2 1293.41    57.3 1280.53    76.9 1266.19
    86.7 1259.95    96.5 1255.01   106.3 1251.14   125.9 1244.77   135.7 1241.93
   145.5 1240.24   150.3 1240.09   155.3 1239.94   160.3 1240.32   165.1 1240.69
   174.9 1242.09   194.4 1245.21     214 1248.75   223.8    1250   282.6 1255.67
   321.7 1258.84   409.8 1265.13   439.2 1267.51     449 1268.17   478.4 1269.18
   488.1 1269.81   497.9 1271.44   507.7 1275.09   517.5 1280.84   527.3 1287.33
#Mann= 3 , 0 , 0
       0      .1       0   150.3    .045       0   160.3      .1       0
Bank Sta=150.3,160.3
XS Rating Curve= 0 ,0
Exp/Cntr=0.3,0.1

Type RM Length L Ch R = 1 ,19045.6 ,351,349.3,347.6
XS GIS Cut Line= 2
     1759081.175       154215.86     1759413.436      154215.448
#Sta/Elev= 29
    10.1 1288.46    30.2 1277.17    40.3 1271.69    50.3 1266.44    60.4 1261.38
    70.5  1256.7    80.5 1253.21    90.6 1251.05   110.8 1248.01   130.9 1244.56
     141 1242.67     151 1240.52   161.1 1238.57   166.2 1238.12   171.2 1237.69
   176.2 1237.96   181.2 1238.24   191.3 1239.98   201.4  1242.1   211.4  1243.9
   221.5 1245.24   231.6 1246.37   241.6 1247.35   251.7 1248.19   261.8 1248.89
   271.8 1249.42   281.9 1249.77     292 1249.99   332.3 1250.61
#Mann= 3 , 0 , 0
       0      .1       0   166.2    .045       0   176.2      .1       0
Bank Sta=166.2,176.2
XS Rating Curve= 0 ,0
Exp/Cntr=0.3,0.1

Type RM Length L Ch R = 1 ,18696.3 ,259.3,262.3,265.4
XS GIS Cut Line= 2
     1759085.591      154578.577     1759450.414      154547.979
#Sta/Elev= 30
     9.9 1250.67    19.8 1248.31    29.7 1246.36    39.6 1244.78    49.5 1243.83
    59.4 1243.35    69.3 1243.04    89.1 1242.84   118.7 1242.07   138.5 1241.88
   148.4 1241.59   158.3 1241.06   168.2 1240.24   178.1 1239.14     188 1237.92
   207.8 1235.02   217.7  1233.8   222.6 1233.61   227.6 1233.41   232.6 1233.82
   237.5 1234.22   247.4 1236.19   257.3 1238.56   277.1 1242.96   286.9 1245.68
   296.8 1249.55   306.7 1254.48   316.6  1259.7   326.5 1264.77   366.1 1284.24
#Mann= 3 , 0 , 0
       0      .1       0   222.6    .045       0   232.6      .1       0
Bank Sta=222.6,232.6
XS Rating Curve= 0 ,0
Exp/Cntr=0.3,0.1

Type RM Length L Ch R = 1 ,18434   ,562.1,563,563.7
XS GIS Cut Line= 2
     1759097.359      154811.593     1759483.365      154823.361
#Sta/Elev= 30
     9.9 1246.57    19.8 1244.11    29.7 1243.15    49.5 1242.42    69.3 1241.47
    79.2 1241.28      99  1241.7   108.9 1241.49   118.8 1240.06   128.7 1236.46
   138.6 1232.17   148.5 1229.85   153.4 1229.75   158.4 1229.64   163.4 1229.99
   168.3 1230.34   178.2 1231.35   227.8    1236   247.6 1238.04   267.4 1240.26
   277.3 1241.46   287.2  1242.8   297.1  1244.4     307 1246.25   316.9 1248.52
   326.8 1251.88   336.7 1256.51   346.6  1261.7   356.5 1267.05   386.2 1283.44
#Mann= 3 , 0 , 0
       0      .1       0   153.4    .045       0   163.4      .1       0
Bank Sta=153.4,163.4
XS Rating Curve= 0 ,0
Exp/Cntr=0.3,0.1

Type RM Length L Ch R = 1 ,17871   ,328.9,330,331
XS GIS Cut Line= 2
     1759108.198      155302.365     1759470.667      155342.377
#Sta/Elev= 25
     9.9 1242.52    19.7 1235.16    29.6 1232.91    88.7 1230.42   108.4 1229.92
   118.3 1229.88   167.6 1230.67   177.4 1230.65   187.3 1230.46   197.1 1230.12
   216.8 1229.08   236.5 1227.77   246.4 1227.02   256.3 1226.15   266.1 1225.13
     276 1224.21   280.8 1224.13   285.8 1224.05   290.8 1225.05   295.7 1226.04
   305.5 1230.95   315.4  1237.1   325.2 1242.32   335.1 1246.15   364.7 1255.77
#Mann= 3 , 0 , 0
       0      .1       0   280.8    .045       0   290.8      .1       0
Bank Sta=280.8,290.8
XS Rating Curve= 0 ,0
Exp/Cntr=0.3,0.1

Type RM Length L Ch R = 1 ,17541.1 ,416.3,424.6,433
XS GIS Cut Line= 2
     1758984.295      155599.863      1759430.91      155673.205
#Sta/Elev= 29
    10.1 1273.59    30.2 1260.31    50.3 1246.87    60.3 1240.31    70.4 1234.31
    80.5 1230.44    90.5 1229.22   191.1 1227.26   241.4 1226.38   251.4 1226.17
   261.5 1225.82   271.6 1225.28   291.7 1223.98   311.8 1222.48   321.8 1221.58
   326.9 1221.26   331.9 1220.95   336.9 1221.16     342 1221.38     352 1223.65
   362.1 1227.48   372.1  1231.7   382.2  1236.2   392.3  1241.5   402.3 1247.47
   422.4 1259.93   432.5 1265.75   442.5  1271.1   452.6 1276.04
#Mann= 3 , 0 , 0
       0      .1       0   326.9    .045       0   336.9      .1       0
Bank Sta=326.9,336.9
XS Rating Curve= 0 ,0
Exp/Cntr=0.3,0.1

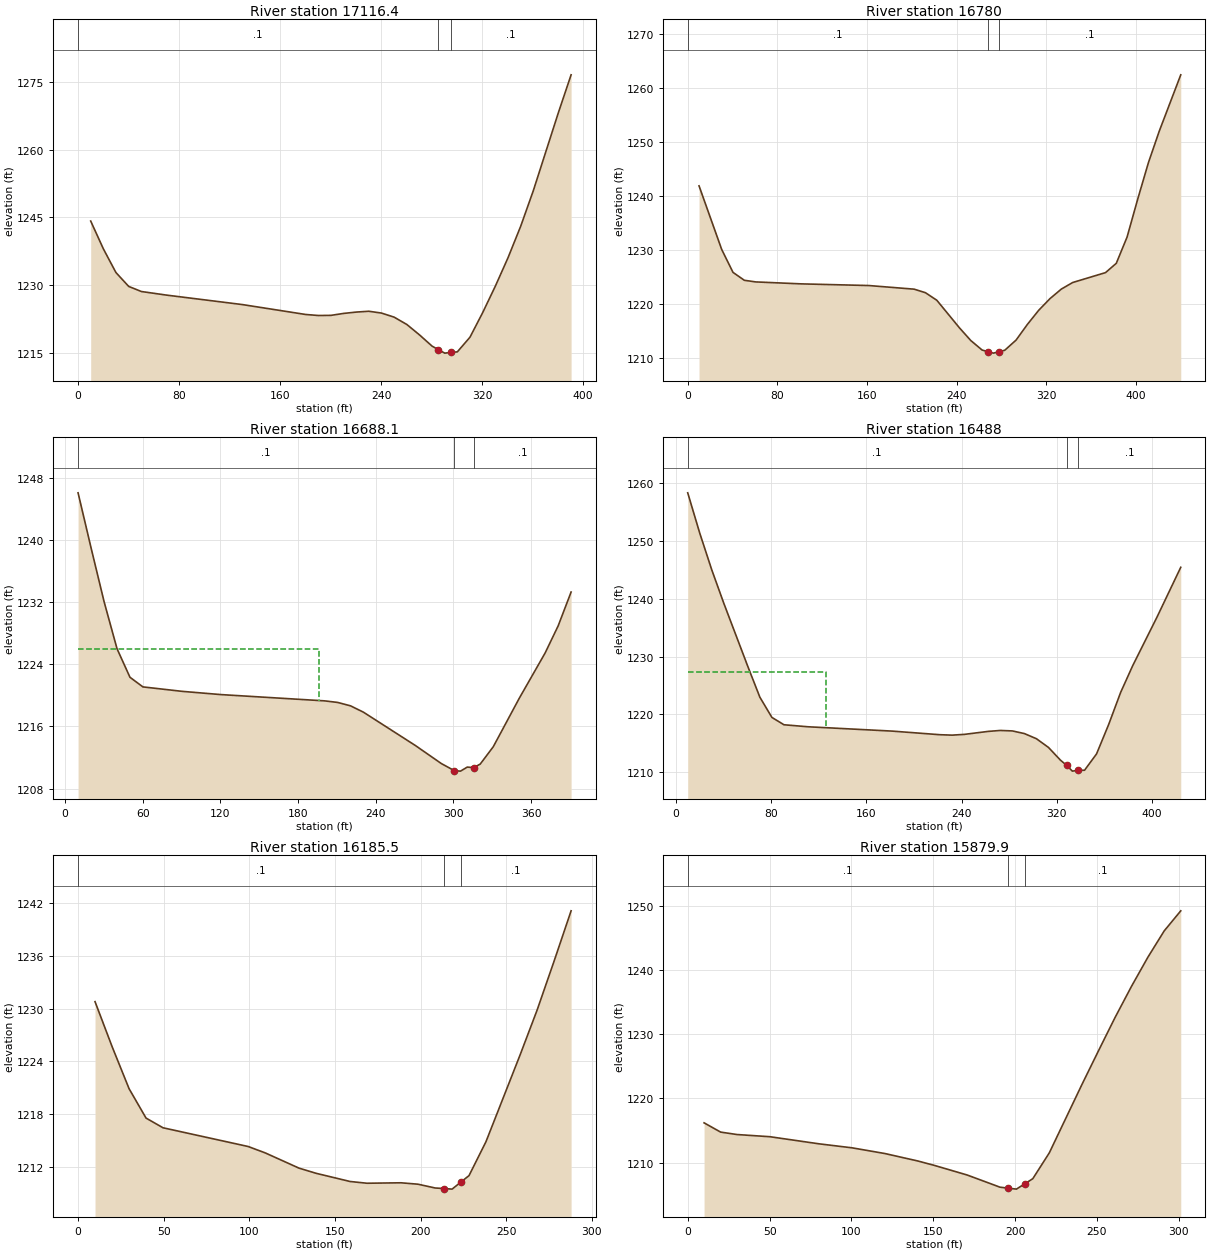
Type RM Length L Ch R = 1 ,17116.4 ,331.4,336.5,341.5
XS GIS Cut Line= 2
     1758902.781      155867.137     1759229.785      156080.644
#Sta/Elev= 30
      10 1244.19      20 1238.05      30 1232.77    40.1  1229.7    50.1 1228.57
    70.1 1227.77   130.2 1225.67   180.2 1223.48   190.3 1223.25   200.3 1223.28
   210.3 1223.71   220.3 1224.01   230.3 1224.19   240.3 1223.79   250.3 1222.89
   260.4 1221.26   270.4 1218.96   280.4 1216.46   285.4 1215.68   290.4 1214.91
   295.4 1215.05   300.4 1215.19   310.4 1218.44   320.4 1223.85   330.5 1229.76
   340.5 1236.03   350.5 1242.98   360.5 1250.86   380.5 1268.28   390.5  1276.6
#Mann= 3 , 0 , 0
       0      .1       0   285.4    .045       0   295.4      .1       0
Bank Sta=285.4,295.4
XS Rating Curve= 0 ,0
Exp/Cntr=0.3,0.1

Type RM Length L Ch R = 1 ,16780   ,92.7,91.9,91
XS GIS Cut Line= 3
     1758730.183      156075.527     1758974.443      156331.087
       1759059.7      156317.958
#Sta/Elev= 30
    10.1 1241.86    30.3 1230.11    40.4 1225.87    50.5 1224.41    60.6 1224.11
     101 1223.75   161.6 1223.44     202 1222.77   212.1 1222.11   222.2 1220.72
   242.4 1215.62   252.5 1213.28   262.6 1211.52   267.7 1211.23   272.7 1210.95
   277.7 1211.21   282.8 1211.48   292.9 1213.36     303 1216.26   313.1 1218.87
   323.2 1221.03   333.3 1222.79   343.4    1224   372.7 1225.83   382.3 1227.55
   391.9 1232.39   401.4 1239.41     411 1246.18   420.6 1251.96   439.8 1262.38
#Mann= 3 , 0 , 0
       0      .1       0   267.7    .045       0   277.7      .1       0
Bank Sta=267.7,277.7
XS Rating Curve= 0 ,0
Exp/Cntr=0.3,0.1

Type RM Length L Ch R = 1 ,16688.1 ,198.1,200.2,202.2
XS GIS Cut Line= 2
     1758666.847      156144.997     1758943.793      156420.848
#Sta/Elev= 24
      10  1246.1      20 1239.04    30.1 1232.08    40.1 1226.02    50.1 1222.34
    60.1  1221.1    90.2 1220.53   120.3 1220.11   200.5  1219.3   210.5  1219.1
   220.5 1218.66   230.5 1217.84   270.6 1213.55   290.7 1211.22   300.7 1210.31
  305.46 1210.25   310.7 1210.77   315.7  1210.7   320.7 1211.16   330.8  1213.4
   350.8 1219.62   370.8 1225.46   380.9 1228.96   390.9 1233.32
#Mann= 3 , 0 , 0
      10      .1       0   300.7    .045       0   315.7      .1       0
#XS Ineff= 2 , 0
          196.46 1226.01
Permanent Ineff=
       F       F
Bank Sta=300.7,315.7
XS Rating Curve= 0 ,0
Exp/Cntr=0.3,0.1

Type RM Length L Ch R = 1 ,16488   ,295.7,302.5,309.3
XS GIS Cut Line= 2
       1758530.1       156240.95       1758799.3      156568.625
#Sta/Elev= 30
    10.1 1258.38    20.2 1251.39    30.3 1245.02    40.4 1239.23    60.6 1228.26
    70.7 1222.94    80.8 1219.44    90.9 1218.17   111.1 1217.82   181.7 1217.07
   222.1 1216.44   232.2 1216.37   242.3  1216.5   262.5 1217.02   272.6 1217.18
   282.7  1217.1   292.8 1216.64   302.9 1215.75     313 1214.24   323.1 1212.03
   328.2 1211.15  333.06 1210.13   338.2 1210.28   343.3 1210.28   353.4 1213.12
   363.5 1218.18   373.6 1223.77   383.7 1228.39   403.9 1236.73   424.1 1245.47
#Mann= 3 , 0 , 0
    10.1      .1       0   328.2    .045       0   338.2      .1       0
#XS Ineff= 2 , 0
          125.84 1227.34
Permanent Ineff=
       F       F
Bank Sta=328.2,338.2
XS Rating Curve= 0 ,0
Exp/Cntr=0.3,0.1

Type RM Length L Ch R = 1 ,16185.5 ,296.9,305.6,314.4
XS GIS Cut Line= 2
     1758392.183      156393.279     1758491.255      156663.555
#Sta/Elev= 23
     9.9 1230.81    19.9 1225.68    29.8  1220.9    39.7 1217.56    49.6 1216.46
    99.3 1214.33   109.2 1213.61     129 1211.87     139 1211.28   158.8 1210.35
   168.7 1210.15   188.6  1210.2   198.5 1210.04   208.5 1209.61   213.4 1209.55
   218.4 1209.48   223.4 1210.26   228.3 1211.02   238.2 1214.88   258.1 1224.74
     268 1229.82   277.9 1235.38   287.9 1241.14
#Mann= 3 , 0 , 0
       0      .1       0   213.4    .045       0   223.4      .1       0
Bank Sta=213.4,223.4
XS Rating Curve= 0 ,0
Exp/Cntr=0.3,0.1

Type RM Length L Ch R = 1 ,15879.9 ,302.7,312.5,322.4
XS GIS Cut Line= 2
     1758187.358      156444.803     1758162.716      156744.982
#Sta/Elev= 23
      10 1216.19    20.1 1214.75    30.1 1214.37    50.2 1214.03    80.3 1212.92
   100.4  1212.3   120.5 1211.41   140.6 1210.25   150.6 1209.57   170.7 1208.07
   190.8 1206.17   195.8 1206.02   200.8 1205.87   205.8 1206.68   210.8 1207.49
   220.9 1211.52     241 1222.25     251 1227.44     261 1232.56   271.1 1237.44
   281.1 1241.97   291.1 1246.08   301.2  1249.2
#Mann= 3 , 0 , 0
       0      .1       0   195.8    .045       0   205.8      .1       0
Bank Sta=195.8,205.8
XS Rating Curve= 0 ,0
Exp/Cntr=0.3,0.1

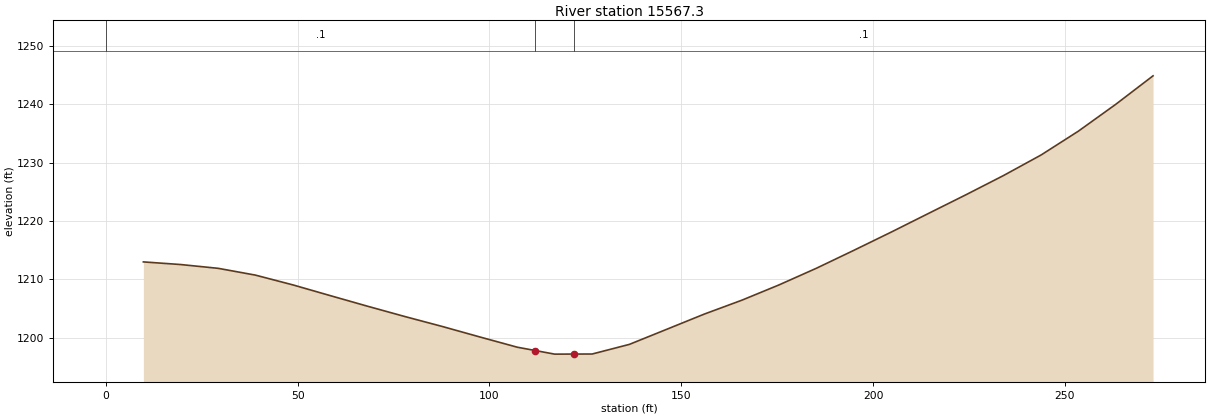
Type RM Length L Ch R = 1 ,15567.3 ,293.1,290.8,288.6
XS GIS Cut Line= 3
     1757981.605      156371.515     1757906.811      156485.702
     1757832.075      156599.923
#Sta/Elev= 30
     9.8 1212.98    19.5 1212.53    29.3 1211.88      39 1210.72    48.8 1209.04
    58.5 1207.21    68.3 1205.38      78 1203.62    87.8 1201.91    97.5 1200.13
   107.3 1198.37     112  1197.8     117 1197.19     122  1197.2   126.8 1197.21
   136.5 1198.86   146.3 1201.46     156 1204.04   165.8 1206.42   175.5 1209.04
   185.3 1211.91     195 1214.96   204.8  1218.1   214.5 1221.29   224.3  1224.5
     234 1227.76   243.8 1231.28   253.5 1235.35   263.3 1239.97     273 1244.84
#Mann= 3 , 0 , 0
       0      .1       0     112    .045       0     122      .1       0
Bank Sta=112,122
XS Rating Curve= 0 ,0
Exp/Cntr=0.3,0.1