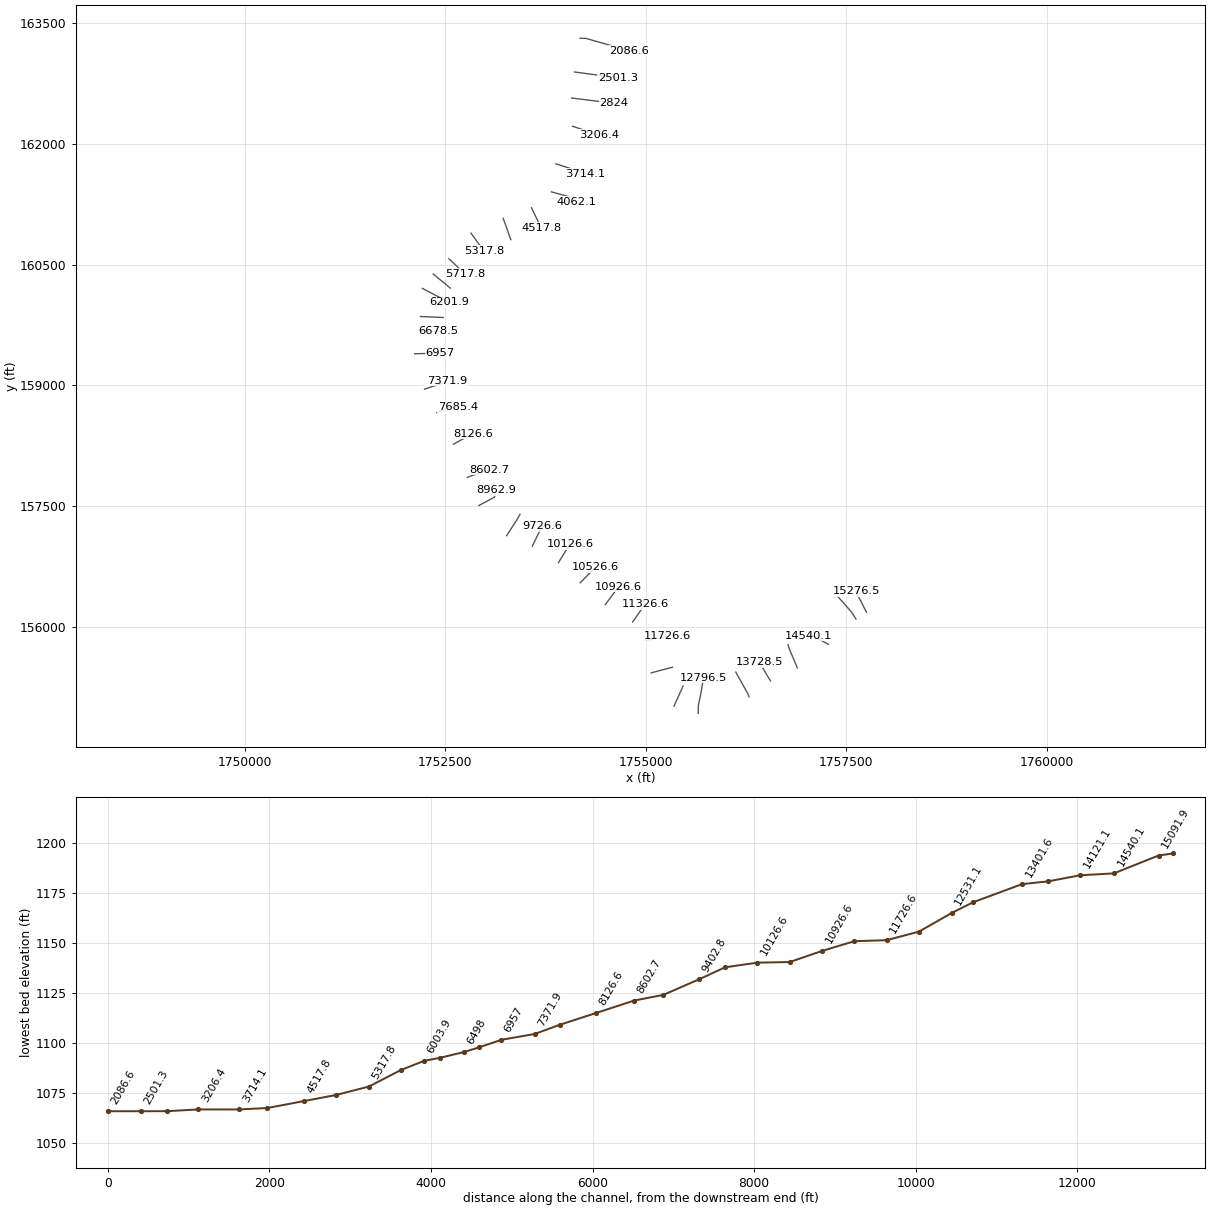
HEC-RAS study Clear Fork A.prj: Clear Fork A

--- Clear Fork A.g01 (geometry) --- (continued)

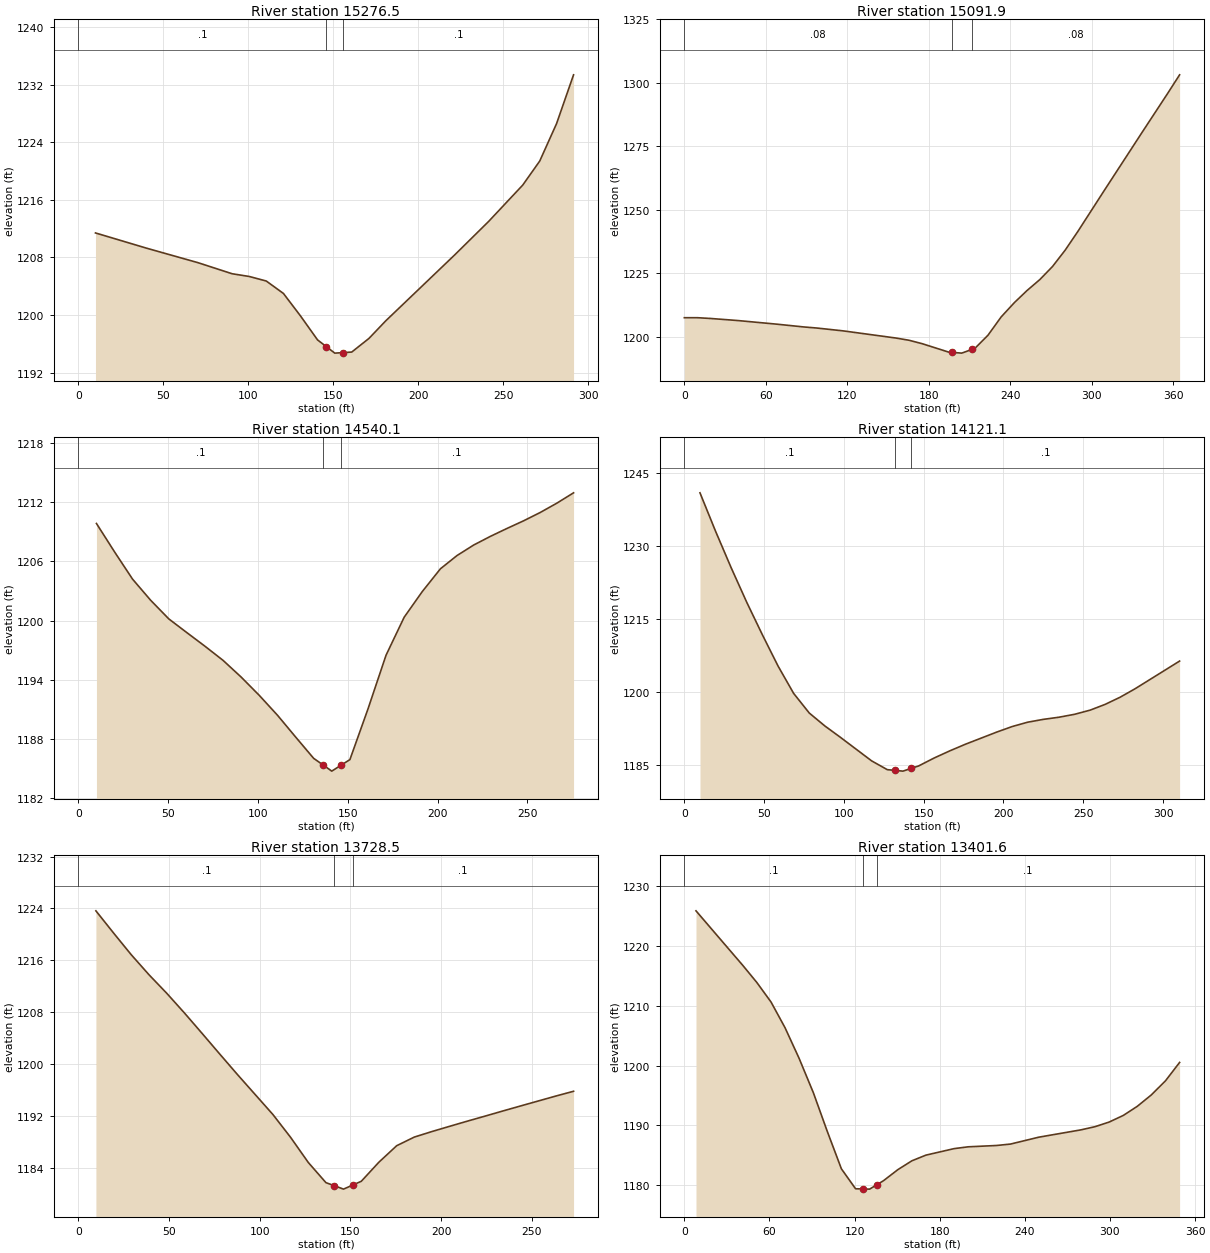
Type RM Length L Ch R = 1 ,15276.5 ,179.8,184.6,189.4
XS GIS Cut Line= 3
     1757750.732       156184.25     1757632.005      156417.225
     1757624.437      156446.163
#Sta/Elev= 21
    10.1  1211.4    40.2 1209.28    70.4 1207.27    90.5 1205.73   100.6 1205.35
   110.6 1204.72   120.7 1202.99   130.7 1199.88   140.8 1196.53   145.9 1195.61
   150.9  1194.7   155.9 1194.77   160.9 1194.85     171 1196.74     181 1199.21
   221.3 1208.31   241.4 1212.99   261.5 1218.05   271.5 1221.39   281.4 1226.59
   291.4 1233.37
#Mann= 3 , 0 , 0
       0      .1       0   145.9    .045       0   155.9      .1       0
Bank Sta=145.9,155.9
XS Rating Curve= 0 ,0
Exp/Cntr=0.3,0.1

Type RM Length L Ch R = 1 ,15091.9 ,543.5,551.9,560.2
XS GIS Cut Line= 4
     1757619.831      156101.456     1757566.256      156183.077
     1757471.571      156293.476     1757389.293       156383.25
#Sta/Elev= 28
       0 1207.58     9.8 1207.58    19.5 1207.27    39.1 1206.48    68.3 1205.03
    87.9 1203.95    97.6 1203.52     117  1202.4   155.8 1199.59   165.5 1198.71
   175.2 1197.36   194.6 1194.07   196.8 1193.97   204.3 1193.65   211.8 1195.09
     214 1195.51   223.7 1200.72   233.4 1207.91   243.1 1213.52   252.4 1218.26
   261.8 1222.55   271.2 1227.73   280.5 1234.14   289.9 1241.54   308.6 1257.04
   336.7  1280.1   355.5 1295.39   364.8 1303.11
#Mann= 3 , 0 , 0
       0     .08       0   196.8    .045       0   211.8     .08       0
Bank Sta=196.8,211.8
XS Rating Curve= 0 ,0
Exp/Cntr=0.3,0.1

Type RM Length L Ch R = 1 ,14540.1 ,432.7,418.9,405.2
XS GIS Cut Line= 3
     1757276.017      155786.785     1757098.648      155882.527
     1757025.656      155895.637
#Sta/Elev= 30
    10.1 1209.85    20.2 1206.96    30.2  1204.2    40.3 1202.05    50.4 1200.16
    60.5 1198.76    70.5 1197.39    80.6 1195.95    90.7 1194.25   100.8 1192.39
   110.9 1190.38   120.9 1188.19     131 1186.01   136.1 1185.36   141.1 1184.71
   146.1 1185.29   151.2 1185.88   161.2 1190.99   171.3 1196.47   181.4 1200.33
   191.5 1202.94   201.6 1205.25   210.8 1206.59   220.1 1207.66   229.4 1208.54
   238.6 1209.34   247.9 1210.12   257.2 1210.97   266.4 1211.91   275.7 1212.96
#Mann= 3 , 0 , 0
       0      .1       0   136.1    .045       0   146.1      .1       0
Bank Sta=136.1,146.1
XS Rating Curve= 0 ,0
Exp/Cntr=0.3,0.1

Type RM Length L Ch R = 1 ,14121.1 ,389.9,392.7,395.5
XS GIS Cut Line= 3
     1756888.784      155493.744     1756789.508      155727.957
     1756773.827       155781.72
#Sta/Elev= 30
     9.8 1240.86    19.6 1232.95    29.4 1225.45    39.1 1218.41    48.9 1211.74
    58.7 1205.34    68.5 1199.71    78.3 1195.68    88.1 1193.02    97.8  1190.7
   117.4 1185.86   127.2 1184.06     132 1183.91     137 1183.76     142  1184.3
   146.8 1184.82   156.5 1186.44   166.3 1187.91   176.1 1189.27   195.7 1191.76
   205.5 1192.91   215.2  1193.8     225 1194.38   234.8 1194.82   244.6 1195.42
   254.4 1196.28   263.7 1197.45   273.1 1198.92   282.4 1200.64   310.4 1206.34
#Mann= 3 , 0 , 0
       0      .1       0     132    .045       0     142      .1       0
Bank Sta=132,142
XS Rating Curve= 0 ,0
Exp/Cntr=0.3,0.1

Type RM Length L Ch R = 1 ,13728.5 ,327.5,326.9,326.3
XS GIS Cut Line= 3
     1756553.317      155332.863     1756483.088      155449.911
      1756412.86      155566.958
#Sta/Elev= 30
     9.7 1223.63    19.5 1220.19    29.2 1216.86      39 1213.77    48.8 1210.91
    58.5 1207.89    68.3 1204.72      78 1201.55    87.7 1198.41    97.5 1195.32
   107.3 1192.23     117 1188.73   126.8 1184.84   136.5 1181.74   141.2 1181.26
   146.2 1180.74   151.2 1181.36     156 1181.95   165.7 1184.89   175.5 1187.43
   185.2 1188.76     195 1189.62   204.7 1190.42   214.5 1191.22   224.2 1191.99
     234 1192.78   243.7 1193.55   253.5 1194.32   263.3 1195.09     273 1195.82
#Mann= 3 , 0 , 0
       0      .1       0   141.2    .045       0   151.2      .1       0
Bank Sta=141.2,151.2
XS Rating Curve= 0 ,0
Exp/Cntr=0.3,0.1

Type RM Length L Ch R = 1 ,13401.6 ,619.7,605.1,590.5
XS GIS Cut Line= 3
      1756287.54      155134.217     1756272.035      155172.401
     1756121.946      155441.219
#Sta/Elev= 30
     8.2 1225.89    41.2 1216.76    51.1  1213.9    61.1 1210.63      71 1206.32
    80.9  1201.2    90.9 1195.48   100.8 1188.95   110.7 1182.72   120.7 1179.38
   125.6 1179.35   130.6 1179.32   135.6 1180.04   140.5 1180.75   150.5 1182.58
   160.4 1184.06   170.3 1185.01   190.2  1186.1   200.1  1186.4     220 1186.62
   229.9 1186.86   249.8 1188.01   279.6 1189.24   289.5 1189.77   299.4 1190.54
   309.4 1191.65   319.3 1193.18   329.2 1195.09   339.2 1197.46   349.1 1200.52
#Mann= 3 , 0 , 0
       0      .1       0   125.6    .045       0   135.6      .1       0
Bank Sta=125.6,135.6
XS Rating Curve= 0 ,0
Exp/Cntr=0.3,0.1

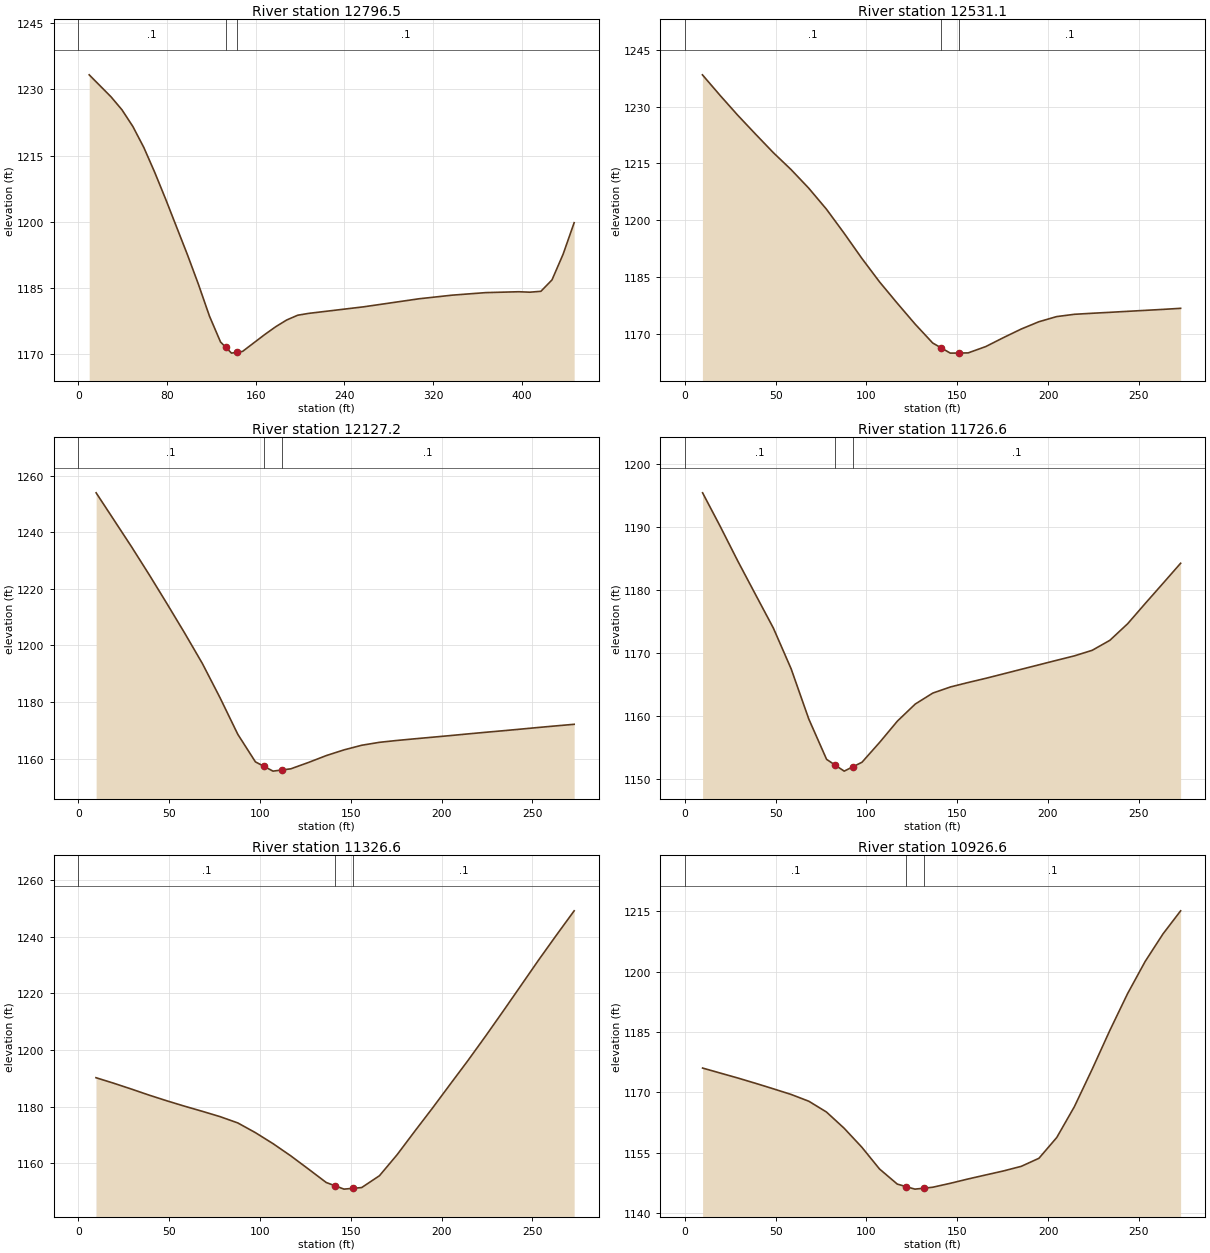
Type RM Length L Ch R = 1 ,12796.5 ,269.8,265.4,261
XS GIS Cut Line= 4
     1755653.557       154928.89     1755655.254      155027.337
     1755685.807      155173.311     1755719.754      155370.206
#Sta/Elev= 30
     9.8 1233.28    29.5  1228.3    39.4 1225.35    49.2 1221.59    59.1 1216.83
    68.9 1211.22    78.8 1205.13    98.5 1192.51   108.4 1185.82   118.3 1178.66
   128.3 1172.79   133.2 1171.54   138.2 1170.26   143.2 1170.45   148.2 1170.65
   168.1 1174.45     178 1176.22   187.9 1177.75   197.9 1178.84   207.8 1179.26
   257.6 1180.75   307.5 1182.57   337.5 1183.39   367.5 1183.96   397.4 1184.16
   407.4 1184.06   417.4 1184.26   427.4 1186.84   437.4 1192.64   447.4 1199.79
#Mann= 3 , 0 , 0
       0      .1       0   133.2    .045       0   143.2      .1       0
Bank Sta=133.2,143.2
XS Rating Curve= 0 ,0
Exp/Cntr=0.3,0.1

Type RM Length L Ch R = 1 ,12531.1 ,421.8,403.9,385.9
XS GIS Cut Line= 3
     1755351.983      155019.791      1755408.21      155144.172
     1755464.437      155268.554
#Sta/Elev= 30
     9.7 1238.41    19.5 1232.94    29.2 1227.71      39 1222.72    48.8 1217.82
    58.5 1213.38    68.2 1208.48      78  1202.9    87.7 1196.57    97.5  1189.9
   107.2 1183.71     117 1178.05   126.8 1172.55   136.5 1167.54   141.2 1166.25
   146.2 1164.87   151.2  1164.9     156 1164.93   165.7  1166.6   175.5 1168.98
   185.3 1171.25     195 1173.17   204.7 1174.52   214.5 1175.13   224.2  1175.4
     234 1175.65   243.7 1175.91   253.5 1176.17   263.3 1176.43     273 1176.71
#Mann= 3 , 0 , 0
       0      .1       0   141.2    .045       0   151.2      .1       0
Bank Sta=141.2,151.2
XS Rating Curve= 0 ,0
Exp/Cntr=0.3,0.1

Type RM Length L Ch R = 1 ,12127.2 ,401.7,400.6,398.7
XS GIS Cut Line= 3
     1755067.598      155431.953     1755199.552      155466.884
     1755331.507      155501.815
#Sta/Elev= 30
     9.8 1253.92    19.5 1244.44    29.3 1234.85      39 1225.01    48.7 1214.86
    58.5 1204.41    68.3  1193.6      78 1181.53    87.8 1168.59    97.5 1158.85
   102.2 1157.26   107.2 1155.57   112.2 1155.99     117 1156.39   126.8 1158.65
   136.5 1161.06   146.3 1163.08     156 1164.71   165.8 1165.75   175.5 1166.41
   185.2 1166.99     195 1167.56   204.8 1168.13   214.5 1168.72   224.3  1169.3
     234 1169.85   243.7 1170.42   253.5 1171.01   263.2 1171.57     273 1172.12
#Mann= 3 , 0 , 0
       0      .1       0   102.2    .045       0   112.2      .1       0
Bank Sta=102.2,112.2
XS Rating Curve= 0 ,0
Exp/Cntr=0.3,0.1

Type RM Length L Ch R = 1 ,11726.6 ,384.6,400,416.3
XS GIS Cut Line= 3
      1755001.78      155833.604     1755135.559      155861.461
     1755270.226      155883.594
#Sta/Elev= 30
     9.8 1195.47    19.5 1190.15    29.3 1184.58      39  1179.3    48.8 1173.99
    58.6 1167.51    68.3 1159.56    78.1 1153.16    82.8 1152.25    87.8 1151.29
    92.8 1152.01    97.6  1152.7   107.4 1155.88   117.1 1159.23   126.9 1161.93
   136.6 1163.68   146.4 1164.66   156.1 1165.36   165.9 1166.03   175.6 1166.74
   185.4 1167.46   195.1 1168.17   204.9 1168.89   214.6 1169.59   224.4 1170.47
   234.1 1172.05   243.9 1174.68   253.6  1177.9   263.4  1181.1   273.1 1184.29
#Mann= 3 , 0 , 0
       0      .1       0    82.8    .045       0    92.8      .1       0
Bank Sta=82.8,92.8
XS Rating Curve= 0 ,0
Exp/Cntr=0.3,0.1

Type RM Length L Ch R = 1 ,11326.6 ,400.6,400,399.4
XS GIS Cut Line= 3
        1754836.      156062.676     1754913.942      156174.735
     1754991.883      156286.795
#Sta/Elev= 30
     9.7  1190.2    19.5 1188.24    29.3 1186.16      39 1184.03    48.8 1182.01
    58.5 1180.12    68.3  1178.3      78 1176.43    87.8  1174.2    97.5 1170.76
   107.3 1166.83     117 1162.54   126.8 1157.84   136.5 1153.12   141.2    1152
   146.3 1150.78   151.2 1151.06     156 1151.33   165.8 1155.52   175.5 1162.94
   185.3 1171.31     195 1179.45   204.7 1187.84   214.5 1196.25   224.3 1204.97
     234 1213.82   243.8 1222.89   253.5 1231.89   263.3 1240.69     273 1249.23
#Mann= 3 , 0 , 0
       0      .1       0   141.2    .045       0   151.2      .1       0
Bank Sta=141.2,151.2
XS Rating Curve= 0 ,0
Exp/Cntr=0.3,0.1

Type RM Length L Ch R = 1 ,10926.6 ,402.9,400,397.1
XS GIS Cut Line= 3
     1754496.115      156280.348     1754577.532      156389.909
     1754658.949      156499.469
#Sta/Elev= 30
     9.8 1176.03    19.5 1174.79    29.3 1173.54      39 1172.23    48.8 1170.86
    58.5 1169.47    68.3 1167.77      78 1165.09    87.7 1161.07    97.5 1156.32
   107.2 1150.92     117 1147.15   121.8 1146.53   126.7  1145.9   131.8 1146.14
   136.5 1146.37   146.3 1147.36     156 1148.43   165.8 1149.44   175.5 1150.43
   185.3 1151.58     195 1153.58   204.8 1158.75   214.5 1166.42   224.3 1175.74
     234 1185.37   243.8 1194.56   253.5 1202.58   263.3 1209.42     273 1215.16
#Mann= 3 , 0 , 0
       0      .1       0   121.8    .045       0   131.8      .1       0
Bank Sta=121.8,131.8
XS Rating Curve= 0 ,0
Exp/Cntr=0.3,0.1

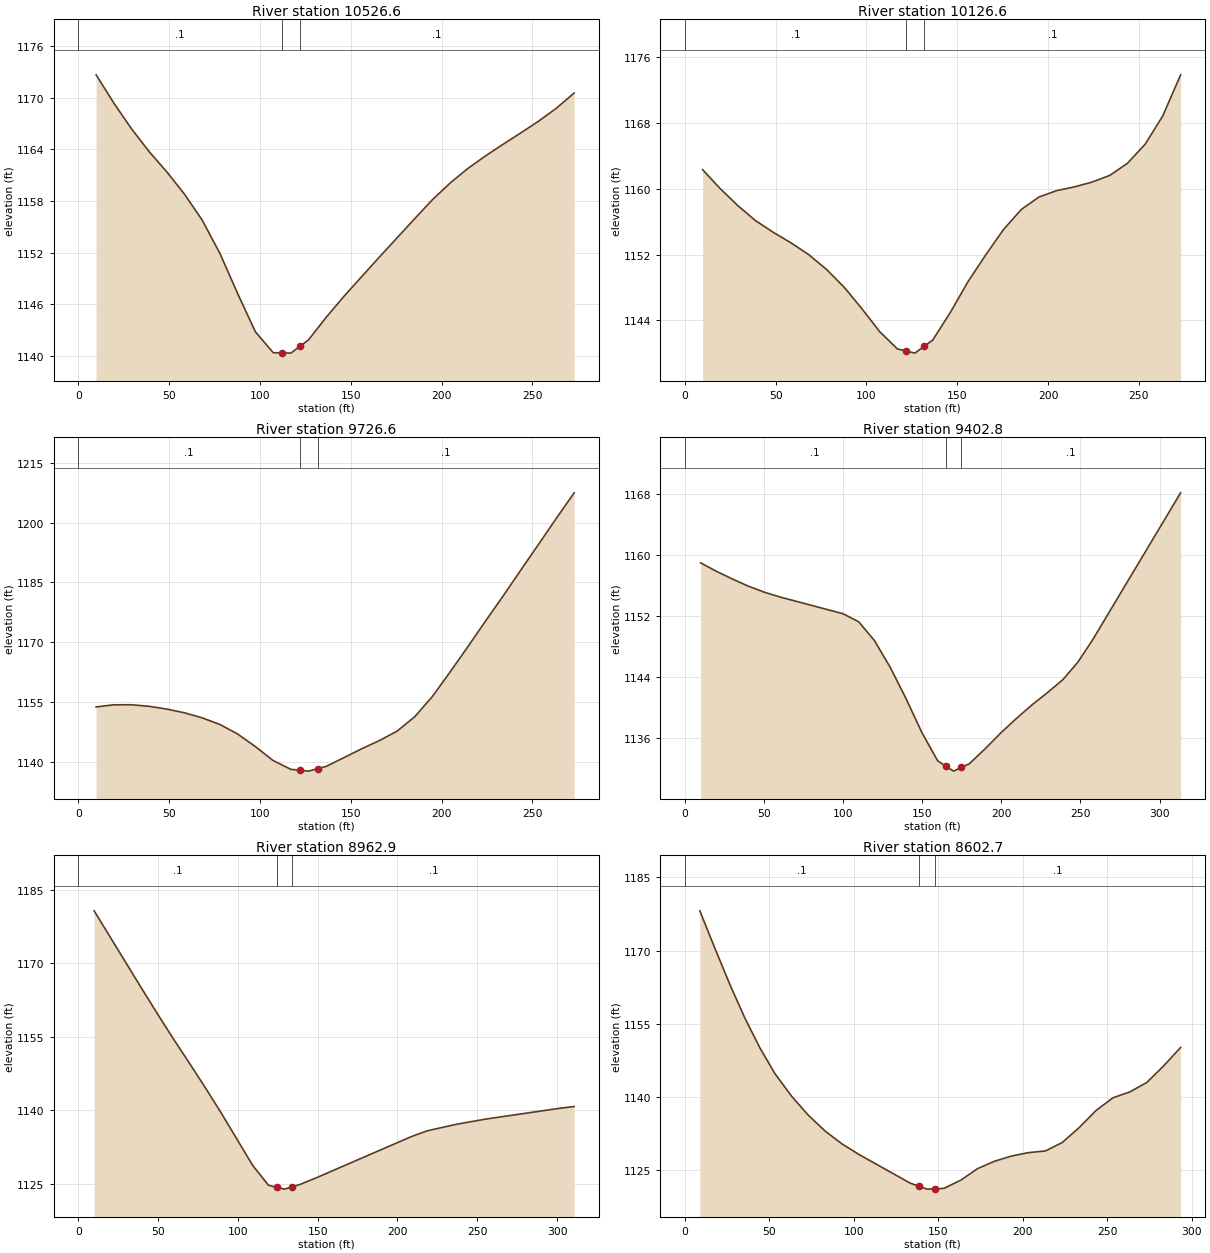
Type RM Length L Ch R = 1 ,10526.6 ,395.5,400,404.5
XS GIS Cut Line= 3
     1754182.691      156550.599     1754278.625      156647.702
     1754374.559      156744.805
#Sta/Elev= 30
     9.8 1172.64    19.5 1169.38    29.2  1166.4      39 1163.73    48.8 1161.36
    58.5 1158.78    68.3 1155.75      78  1151.9    87.7 1147.27    97.5 1142.82
   107.3  1140.4     112 1140.38     117 1140.35     122 1141.14   126.7 1141.88
   136.5 1144.51   146.3 1146.95     156 1149.22   165.7 1151.48   175.5 1153.73
   185.3 1155.97     195 1158.16   204.8  1160.1   214.5 1161.78   224.3 1163.25
     234  1164.6   243.8 1165.93   253.5 1167.27   263.3 1168.78     273 1170.53
#Mann= 3 , 0 , 0
       0      .1       0     112    .045       0     122      .1       0
Bank Sta=112,122
XS Rating Curve= 0 ,0
Exp/Cntr=0.3,0.1

Type RM Length L Ch R = 1 ,10126.6 ,397.9,400,402.1
XS GIS Cut Line= 3
     1753910.683      156800.224     1753982.831      156916.099
      1754054.98      157031.973
#Sta/Elev= 30
     9.8 1162.29    19.5 1159.99    29.3 1157.91      39  1156.1    48.8 1154.68
    58.5 1153.41    68.2 1151.99      78  1150.2    87.8 1148.02    97.5 1145.43
   107.3 1142.65     117 1140.56   121.8  1140.3   126.7 1140.04   131.8 1140.87
   136.5 1141.62   146.3 1145.01     156 1148.73   165.8 1151.99   175.5 1155.03
   185.3 1157.47     195 1158.97   204.8 1159.75   214.5  1160.2   224.2 1160.78
     234 1161.59   243.7 1163.06   253.5 1165.38   263.2 1168.82     273 1173.79
#Mann= 3 , 0 , 0
       0      .1       0   121.8    .045       0   131.8      .1       0
Bank Sta=121.8,131.8
XS Rating Curve= 0 ,0
Exp/Cntr=0.3,0.1

Type RM Length L Ch R = 1 ,9726.6  ,326.2,323.8,321.3
XS GIS Cut Line= 3
     1753585.714      157005.638      1753645.31       157128.44
     1753704.906      157251.243
#Sta/Elev= 30
     9.8  1153.8    19.5 1154.33    29.3 1154.34      39 1153.95    48.7 1153.26
    58.5 1152.32    68.2 1151.06      78 1149.39    87.7 1147.02    97.5 1143.86
   107.2 1140.38     117 1138.16   121.8 1137.94   126.7 1137.71   131.8 1138.33
   136.5  1138.9   146.2 1141.08     156 1143.31   165.7 1145.35   175.5 1147.73
   185.2 1151.33     195 1156.45   204.7 1162.56   214.5  1168.9   224.2 1175.31
     234 1181.67   243.7 1188.15   253.5 1194.61   263.2 1201.07     273 1207.45
#Mann= 3 , 0 , 0
       0      .1       0   121.8    .045       0   131.8      .1       0
Bank Sta=121.8,131.8
XS Rating Curve= 0 ,0
Exp/Cntr=0.3,0.1

Type RM Length L Ch R = 1 ,9402.8  ,450.1,439.9,429.7
XS GIS Cut Line= 3
     1753264.983      157134.928     1753389.983      157327.637
      1753431.69       157400.12
#Sta/Elev= 26
      10 1158.94      20 1157.83      30 1156.83    39.9 1155.91    49.9 1155.12
    59.9 1154.48    99.9 1152.28   109.9 1151.22   119.8 1148.77   129.8 1145.26
   139.8 1141.16   149.8 1136.72   159.8 1133.01   164.8 1132.33   169.8 1131.66
   174.8 1132.15   179.8 1132.63   189.8 1134.59   199.7 1136.67   209.7 1138.59
   219.7 1140.39   229.7 1142.03     239 1143.66   248.3 1145.91   257.6 1148.82
   313.3 1168.11
#Mann= 3 , 0 , 0
       0      .1       0   164.8    .045       0   174.8      .1       0
Bank Sta=164.8,174.8
XS Rating Curve= 0 ,0
Exp/Cntr=0.3,0.1

Type RM Length L Ch R = 1 ,8962.9  ,363.7,360.2,356.7
XS GIS Cut Line= 3
     1752919.497      157509.928     1753112.593      157612.432
     1753139.235      157700.569
#Sta/Elev= 20
     9.9 1180.71    39.7 1164.87    49.7 1159.63    59.6 1154.56    69.6 1149.64
    79.5 1144.66    89.4 1139.54   109.3 1128.74   119.2  1124.7   124.2 1124.31
   129.2 1123.92   134.2 1124.41   139.1  1124.9   149.1 1126.23   208.7 1134.64
   218.6 1135.82     237 1137.16   255.4 1138.22   301.5 1140.41   310.7 1140.78
#Mann= 3 , 0 , 0
       0      .1       0   124.2    .045       0   134.2      .1       0
Bank Sta=124.2,134.2
XS Rating Curve= 0 ,0
Exp/Cntr=0.3,0.1

Type RM Length L Ch R = 1 ,8602.7  ,472.3,476.1,479.9
XS GIS Cut Line= 3
     1752775.171      157858.333     1752824.454      157878.495
     1753052.949      157952.419
#Sta/Elev= 30
     8.9 1178.15    17.7 1170.57    26.6 1163.11    35.5  1156.2    44.4 1150.08
    53.2 1144.84    63.3  1140.1    73.3 1136.17    83.3 1132.92    93.3  1130.3
   103.3 1128.15   133.3 1122.33   138.3 1121.71   143.3 1121.09   148.3 1121.16
   153.3 1121.24   163.3 1122.93   173.3  1125.3   183.3 1126.81   193.3 1127.87
   203.3 1128.57   213.4 1128.92   223.4 1130.66   233.4 1133.72   243.4 1137.23
   253.4 1139.82   263.4 1141.03   273.4 1142.96   283.4 1146.37   293.4 1150.14
#Mann= 3 , 0 , 0
       0      .1       0   138.3    .045       0   148.3      .1       0
Bank Sta=138.3,148.3
XS Rating Curve= 0 ,0
Exp/Cntr=0.3,0.1

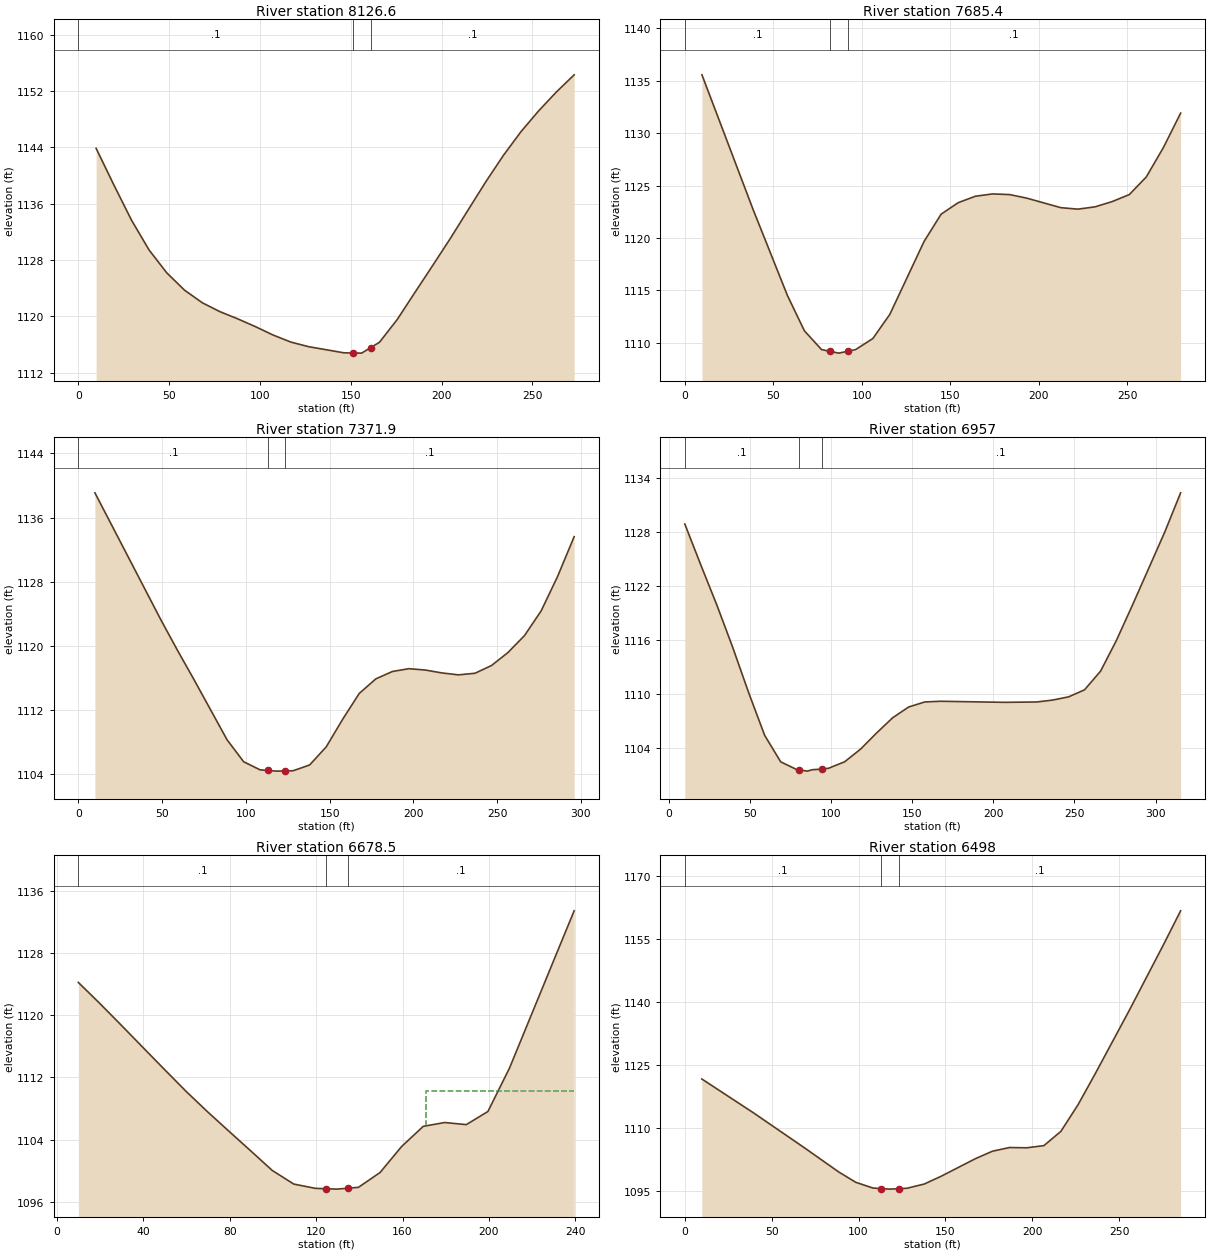
Type RM Length L Ch R = 1 ,8126.6  ,442.3,441.1,440
XS GIS Cut Line= 3
     1752603.422      158271.701     1752723.038       158337.46
     1752842.654      158403.219
#Sta/Elev= 30
     9.8 1143.86    19.5  1138.7    29.3 1133.66      39 1129.42    48.7 1126.19
    58.5 1123.73    68.3 1121.94      78 1120.68    87.8 1119.66    97.5 1118.56
   107.2 1117.37     117 1116.37   126.7 1115.72   136.5 1115.28   146.3 1114.84
     151 1114.82     156  1114.8     161 1115.59   165.8 1116.34   175.5 1119.54
   185.2 1123.36     195 1127.19   204.8 1131.06   214.5 1135.07   224.3 1139.09
     234 1142.84   243.7 1146.22   253.5 1149.19   263.2 1151.85     273 1154.29
#Mann= 3 , 0 , 0
       0      .1       0     151    .045       0     161      .1       0
Bank Sta=151,161
XS Rating Curve= 0 ,0
Exp/Cntr=0.3,0.1

Type RM Length L Ch R = 1 ,7685.4  ,316.1,313.5,311
XS GIS Cut Line= 3
     1752394.241      158662.773      1752533.79      158729.302
     1752659.446      158727.543
#Sta/Elev= 26
     9.7 1135.55    38.6 1122.72      58 1114.53    67.6 1111.16    77.3 1109.37
      82  1109.2      87 1109.03      92  1109.2    96.6 1109.37   106.3 1110.42
   115.9 1112.72   135.3 1119.68   144.9 1122.27   154.6 1123.37   164.3 1123.98
   173.9  1124.2   183.6 1124.14   193.3  1123.8   212.6 1122.89   222.3 1122.75
   231.9 1122.97   241.6 1123.47   251.3 1124.14   260.9 1125.82   270.6 1128.63
   280.3  1131.9
#Mann= 3 , 0 , 0
       0      .1       0      82    .045       0      92      .1       0
Bank Sta=82,92
XS Rating Curve= 0 ,0
Exp/Cntr=0.3,0.1

Type RM Length L Ch R = 1 ,7371.9  ,420.8,414.9,409
XS GIS Cut Line= 3
     1752241.842      158955.053     1752438.737      159019.553
     1752518.514      159058.592
#Sta/Elev= 28
     9.9 1139.09    49.3 1123.24    59.2 1119.44    69.1 1115.77    88.8 1108.28
    98.7 1105.54   108.5 1104.53   113.4 1104.45   118.4 1104.37   123.4 1104.39
   128.3 1104.42   138.1 1105.14     148  1107.4   157.9 1110.87   167.7 1114.06
   177.6 1115.88   187.5  1116.8   197.3 1117.15   207.2 1116.98   217.1 1116.62
   226.9 1116.38   236.8 1116.58   246.7 1117.55   256.5 1119.17   266.4 1121.29
   276.3 1124.36   286.1 1128.65     296 1133.62
#Mann= 3 , 0 , 0
       0      .1       0   113.4    .045       0   123.4      .1       0
Bank Sta=113.4,123.4
XS Rating Curve= 0 ,0
Exp/Cntr=0.3,0.1

Type RM Length L Ch R = 1 ,6957    ,279.6,278.6,277.5
XS GIS Cut Line= 2
      1752119.77      159393.906     1752435.028      159401.569
#Sta/Elev= 30
     9.9 1128.88    19.7 1124.36    29.6  1119.9    39.4 1115.19    49.3 1110.12
    59.1 1105.41      69 1102.46    78.8 1101.61   80.09 1101.59   85.29 1101.43
    88.7 1101.59   94.25 1101.65    98.5 1101.75   108.4 1102.47   118.3 1103.89
   128.1 1105.67     138 1107.36   147.8 1108.55   157.7 1109.11   167.5 1109.19
   206.9 1109.07   226.7 1109.11   236.5 1109.32   246.4 1109.68   256.2 1110.46
   266.1 1112.54   275.9 1115.97   285.8  1119.9   305.5 1127.93   315.4 1132.34
#Mann= 3 , 0 , 0
     9.9      .1       0   80.09    .045       0   94.25      .1       0
Bank Sta=80.09,94.25
XS Rating Curve= 0 ,0
Exp/Cntr=0.3,0.1

Type RM Length L Ch R = 1 ,6678.5  ,180.9,180.4,180
XS GIS Cut Line= 2
     1752177.852      159676.877     1752417.181      159671.785
#Sta/Elev= 26
      10 1124.25    19.9 1121.55    29.9 1118.73    39.9 1115.87    49.9 1113.02
    59.8 1110.23    69.8 1107.58    79.8 1105.05    89.8 1102.54    99.7 1100.03
   109.7 1098.27   119.7 1097.72   124.7 1097.67   129.7 1097.62   134.7 1097.74
   139.6 1097.85   149.6 1099.76   159.6 1103.12   169.6 1105.71   179.5  1106.2
   189.5 1105.93   199.5 1107.62   209.5 1113.22   219.4 1119.93   229.4 1126.71
   239.4 1133.47
#Mann= 3 , 0 , 0
      10      .1       0   124.7    .045       0   134.7      .1       0
#XS Ineff= 2 , 0
                          170.72          1110.2
Permanent Ineff=
       F       F
Bank Sta=124.7,134.7
XS Rating Curve= 0 ,0
Exp/Cntr=0.3,0.1

Type RM Length L Ch R = 1 ,6498    ,304.8,296.1,287.4
XS GIS Cut Line= 2
     1752190.921      159856.356     1752476.079      159844.475
#Sta/Elev= 23
     9.8 1121.64    39.4  1113.6    68.9 1105.21    88.6 1099.46    98.4 1096.99
   108.3 1095.62   113.1 1095.49   118.1 1095.36   123.1 1095.46   127.9 1095.57
   137.8 1096.57   147.6 1098.44   167.3 1102.63   177.1 1104.41     187 1105.29
   196.8 1105.22   206.7 1105.74   216.5 1109.15   226.4 1115.53   236.2 1122.86
   255.9 1138.05   275.6 1153.73   285.4 1161.76
#Mann= 3 , 0 , 0
       0      .1       0   113.1    .045       0   123.1      .1       0
Bank Sta=113.1,123.1
XS Rating Curve= 0 ,0
Exp/Cntr=0.3,0.1

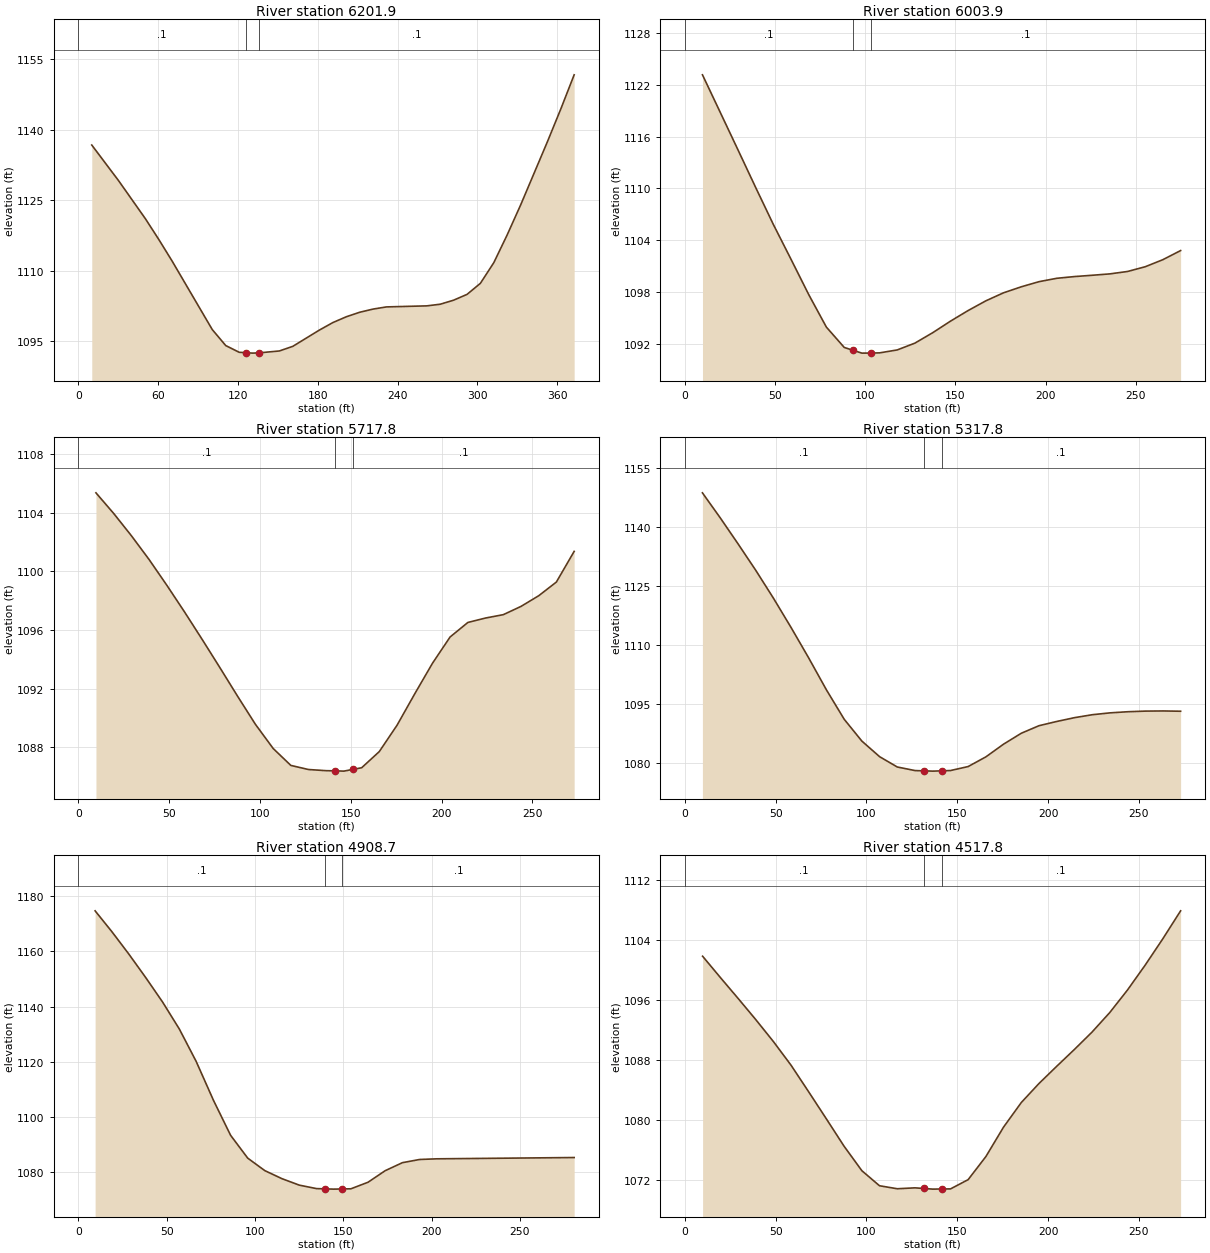
Type RM Length L Ch R = 1 ,6201.9  ,202.2,198,193.8
XS GIS Cut Line= 2
     1752214.684      160206.015     1752545.672       160034.58
#Sta/Elev= 30
    10.1 1136.74    30.2 1129.18    50.4 1121.07    60.4 1116.69    70.5 1112.06
   100.7 1097.48   110.8 1094.09   120.9 1092.66     126 1092.57     131 1092.48
     136 1092.54   151.1 1092.94   161.2 1093.92   181.3  1097.4   191.4 1098.99
   201.5 1100.22   211.6 1101.18   221.6 1101.85   231.7 1102.31   261.9 1102.53
     272 1102.88   282.1 1103.74   292.2 1104.98   302.2 1107.32   312.3 1111.72
   322.4 1117.65   332.5 1124.01   352.6 1137.44   362.7 1144.43   372.7 1151.67
#Mann= 3 , 0 , 0
       0      .1       0     126    .045       0     136      .1       0
Bank Sta=126,136
XS Rating Curve= 0 ,0
Exp/Cntr=0.3,0.1

Type RM Length L Ch R = 1 ,6003.9  ,286.5,286.1,285.5
XS GIS Cut Line= 2
     1752350.474      160384.238     1752562.645      160209.409
#Sta/Elev= 30
     9.8 1123.14    19.6 1118.82    29.5 1114.45    39.3  1110.1    49.1 1105.82
    58.9 1101.79    68.7 1097.71    78.5 1093.94    88.4 1091.59    93.2 1091.26
    98.2 1090.93   103.2 1090.94     108 1090.96   117.8  1091.3   127.6 1092.09
   137.5  1093.3   147.3 1094.63   157.1 1095.86   166.9 1096.98   176.7 1097.91
   186.6 1098.61   196.4  1099.2   206.2 1099.59     216 1099.79   225.8 1099.94
   235.6  1100.1   245.5 1100.38   255.3 1100.93   265.1 1101.75   274.9  1102.8
#Mann= 3 , 0 , 0
       0      .1       0    93.2    .045       0   103.2      .1       0
Bank Sta=93.2,103.2
XS Rating Curve= 0 ,0
Exp/Cntr=0.3,0.1

Type RM Length L Ch R = 1 ,5717.8  ,403.8,400,396.2
XS GIS Cut Line= 3
     1752545.753      160574.323     1752645.271      160480.897
     1752744.789      160387.472
#Sta/Elev= 30
     9.7 1105.35    19.5 1103.94    29.2 1102.43      39  1100.8    48.8 1099.04
    58.5 1097.23    68.2 1095.36      78 1093.43    87.7 1091.49    97.5 1089.58
   107.3 1087.93     117 1086.78   126.7  1086.5   136.5 1086.42   141.2 1086.41
   146.2 1086.39   151.2 1086.51     156 1086.62   165.7 1087.72   175.5 1089.52
   185.2 1091.65     195 1093.74   204.7 1095.53   214.5 1096.52   224.2 1096.82
     234 1097.05   243.7 1097.61   253.5 1098.34   263.2 1099.27     273 1101.36
#Mann= 3 , 0 , 0
       0      .1       0   141.2    .045       0   151.2      .1       0
Bank Sta=141.2,151.2
XS Rating Curve= 0 ,0
Exp/Cntr=0.3,0.1

Type RM Length L Ch R = 1 ,5317.8  ,414.9,409.2,403.5
XS GIS Cut Line= 3
     1752820.971      160891.759     1752900.976      160781.164
     1752980.981      160670.568
#Sta/Elev= 30
     9.7 1148.77    19.5 1142.42    29.2 1135.89      39 1129.13    48.8    1122
    58.5 1114.56    68.2 1106.83      78 1098.69    87.8 1091.21    97.5 1085.68
   107.3 1081.71     117  1079.1   126.8 1078.19   131.5 1078.12   136.5 1078.05
   141.5 1078.12   146.3  1078.2     156 1079.21   165.8 1081.68   175.5  1084.9
   185.3 1087.68     195 1089.59   204.8 1090.67   214.5 1091.63   224.3 1092.38
     234 1092.85   243.8 1093.14   253.5  1093.3   263.3 1093.34     273 1093.27
#Mann= 3 , 0 , 0
       0      .1       0   131.5    .045       0   141.5      .1       0
Bank Sta=131.5,141.5
XS Rating Curve= 0 ,0
Exp/Cntr=0.3,0.1

Type RM Length L Ch R = 1 ,4908.7  ,388.6,390.8,393
XS GIS Cut Line= 3
     1753222.104       161074.92     1753245.602      161012.455
     1753317.286      160810.842
#Sta/Elev= 24
     9.5 1174.74    19.1 1167.09    28.6 1159.05    38.1 1150.58    47.7 1141.66
    57.2 1131.85    66.7 1120.14    76.5 1106.02    86.2 1093.33    95.9 1085.04
   105.6  1080.5   115.4 1077.56   125.1 1075.25   134.8 1073.99   139.5  1073.9
   144.5  1073.8   149.5 1073.86   154.3 1073.92     164 1076.29   173.7 1080.48
   183.5  1083.4   193.2 1084.55   202.9 1084.79   280.7 1085.26
#Mann= 3 , 0 , 0
       0      .1       0   139.5    .045       0   149.5      .1       0
Bank Sta=139.5,149.5
XS Rating Curve= 0 ,0
Exp/Cntr=0.3,0.1

Type RM Length L Ch R = 1 ,4517.8  ,438.3,455.8,473.2
XS GIS Cut Line= 3
     1753575.161      161206.547     1753634.657      161083.695
     1753694.153      160960.843
#Sta/Elev= 30
     9.8 1101.81    19.5    1099    29.3 1096.21      39  1093.4    48.8 1090.45
    58.5 1087.31    68.2 1083.77      78 1080.15    87.7 1076.53    97.5 1073.27
   107.2 1071.27     117 1070.87   126.7 1070.99   131.5 1070.91   136.5 1070.82
   141.5 1070.84   146.3 1070.85     156 1072.08   165.8 1075.16   175.5 1079.07
   185.3 1082.35     195 1084.87   204.8 1087.17   214.5  1089.4   224.2 1091.71
     234 1094.32   243.7  1097.3   253.5 1100.63   263.2 1104.13     273 1107.85
#Mann= 3 , 0 , 0
       0      .1       0   131.5    .045       0   141.5      .1       0
Bank Sta=131.5,141.5
XS Rating Curve= 0 ,0
Exp/Cntr=0.3,0.1

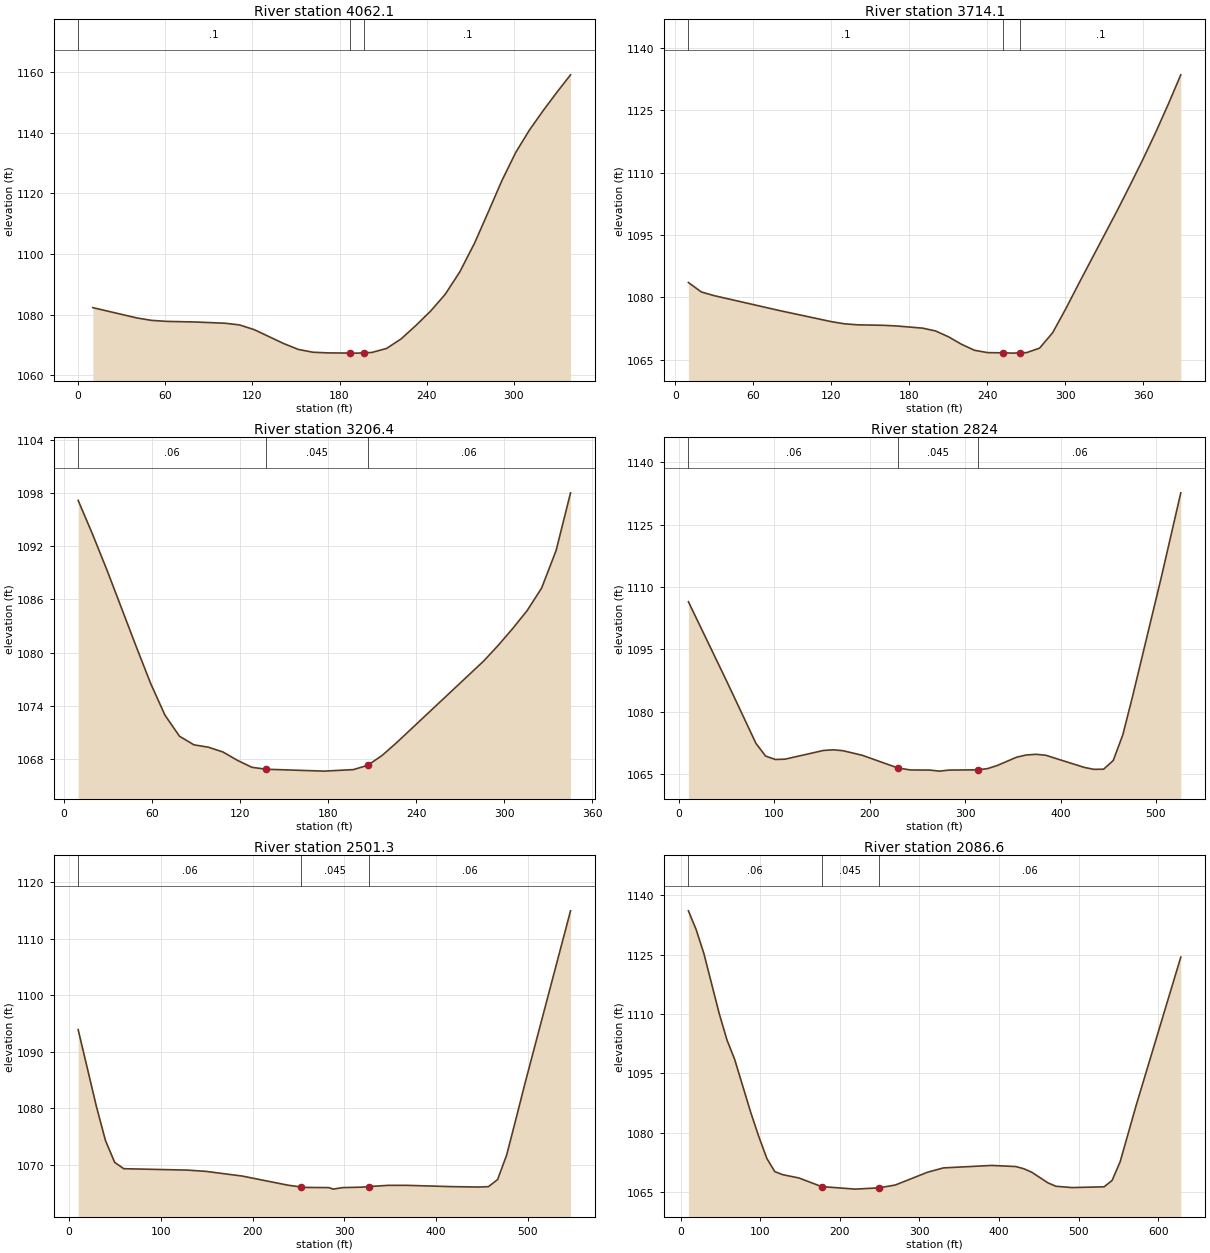
Type RM Length L Ch R = 1 ,4062.1  ,349,347.9,346.9
XS GIS Cut Line= 3
     1753823.792      161404.358     1754086.884      161331.371
     1754131.016      161282.147
#Sta/Elev= 30
    10.1 1082.33    40.4 1078.93    50.6 1078.13    60.7  1077.8    80.9 1077.59
   101.1 1077.19   111.2 1076.62   121.3 1075.06   141.6 1070.47   151.7 1068.53
   161.8 1067.61   171.9  1067.4   187.1 1067.34   192.1 1067.32   197.1 1067.43
   202.2 1067.53   212.4 1068.86   222.5 1072.04   232.6 1076.45   242.7 1081.17
   252.8 1086.74   262.9 1094.19     273 1103.62   282.5 1113.95   291.9 1124.33
   301.4 1133.58   310.8 1140.94   320.3 1147.38   329.7  1153.4   339.1 1159.16
#Mann= 3 , 0 , 0
       0      .1       0   187.1    .045       0   197.1      .1       0
Bank Sta=187.1,197.1
XS Rating Curve= 0 ,0
Exp/Cntr=0.3,0.1

Type RM Length L Ch R = 1 ,3714.1  ,508,507.7,507.5
XS GIS Cut Line= 3
     1753878.107      161752.319     1754183.634      161655.569
     1754245.979      161627.009
#Sta/Elev= 29
      10  1083.6      20 1081.32      30 1080.43    80.1 1076.86   120.2 1074.18
   130.2 1073.67   140.2 1073.43   160.2 1073.31   170.3 1073.15   190.3 1072.63
   200.3 1071.95   210.3 1070.54   220.3 1068.74   230.3  1067.3   240.4 1066.74
  252.33 1066.69  260.39 1066.62   265.4 1066.72   270.4 1066.74   280.4 1067.83
   290.4 1071.51   300.4  1077.2   310.5 1083.31   340.1 1100.88   349.9 1106.91
   359.7 1113.07   369.5 1119.53   379.3 1126.37   389.1 1133.55
#Mann= 3 , 0 , 0
      10      .1       0  252.33    .045       0   265.4      .1       0
Bank Sta=252.33,265.4
XS Rating Curve= 0 ,0
Exp/Cntr=0.3,0.1

Type RM Length L Ch R = 1 ,3206.4  ,378.5,382.4,386.3
XS GIS Cut Line= 2
     1754086.884      162219.096     1754414.477      162110.464
#Sta/Elev= 25
     9.9 1097.19    19.7 1093.36    29.6 1089.28    49.3 1080.73    59.2 1076.53
      69 1072.93    78.9 1070.55    88.7 1069.58    98.6 1069.31   108.5 1068.77
   118.3 1067.83   128.2 1067.04     1381066.822  177.36 1066.61   197.2 1066.78
     2071067.265   216.9 1068.39   226.8 1069.84     286 1079.05   295.8  1080.8
   305.7 1082.71   315.6 1084.75   325.4 1087.28   335.3 1091.54   345.1 1098.04
#Mann= 3 , 0 , 0
     9.9     .06       0     138    .045       0     207     .06       0
Bank Sta=138,207
XS Rating Curve= 0 ,0
Exp/Cntr=0.3,0.1

Type RM Length L Ch R = 1 ,2824    ,322.9,322.7,322.5
XS GIS Cut Line= 2
     1754076.695      162569.355     1754598.648      162504.391
#Sta/Elev= 30
    10.1 1106.45    50.6 1087.17    80.9  1072.4      91 1069.37   101.2 1068.55
   111.3 1068.62   151.7 1070.72   161.8 1070.87     172 1070.66   192.2 1069.56
     2301066.475   242.8 1066.03     263    1066  273.27 1065.75   283.2    1066
     3141066.063   323.7 1066.37   333.8 1067.11     354  1069.1   364.1 1069.63
   374.3 1069.79   384.4 1069.57   424.8 1066.65   434.9 1066.18   445.1 1066.21
   455.2  1068.3   465.3 1074.51   475.4 1083.64   505.8 1112.55     526 1132.62
#Mann= 3 , 0 , 0
    10.1     .06       0     230    .045       0     314     .06       0
Bank Sta=230,314
XS Rating Curve= 0 ,0
Exp/Cntr=0.3,0.1

Type RM Length L Ch R = 1 ,2501.3  ,417.5,414.7,411.9
XS GIS Cut Line= 2
     1754110.647      162892.952     1754652.108      162819.965
#Sta/Elev= 26
     9.9 1093.92    29.8 1080.33    39.7  1074.3    49.7 1070.46    59.6 1069.34
   129.1 1069.09     149 1068.87   188.7 1068.04   238.4 1066.43     2531066.104
   258.3 1066.03   283.1    1066  287.85 1065.73     298    1066   317.9 1066.07
     327 1066.18   347.7  1066.4   367.6  1066.4   417.2 1066.17     447  1066.1
     457 1066.17   466.9 1067.42   476.8 1071.76   486.8 1078.05   496.7 1084.38
   546.4 1114.92
#Mann= 3 , 0 , 0
     9.9     .06       0     253    .045       0     327     .06       0
Bank Sta=253,327
XS Rating Curve= 0 ,0
Exp/Cntr=0.3,0.1

Type RM Length L Ch R = 1 ,2086.6  ,83.1,83.6,90.9
XS GIS Cut Line= 4
     1754181.937      163310.505     1754249.832      163310.505
     1754774.319      163162.834     1754789.595      163159.439
#Sta/Elev= 30
     9.7 1136.08    19.4 1131.36    29.1 1125.31    48.5 1110.03    58.2  1103.4
    67.9 1098.47    88.1 1085.05    98.2 1078.97   108.3 1073.45   118.3 1070.13
   128.4 1069.35   148.6 1068.53     1771066.355   219.3 1065.71     2491066.038
   269.7 1066.75   310.1 1069.98   330.2 1071.08   390.8  1071.7   421.1 1071.42
   431.1 1070.87   441.2 1069.97   461.4  1067.3   471.5 1066.44   491.7  1066.1
   532.1  1066.3   542.1 1067.92   552.2 1072.63   572.4 1086.95   628.4 1124.38
#Mann= 3 , 0 , 0
     9.7     .06       0     177    .045       0     249     .06       0
Bank Sta=177,249
XS Rating Curve= 0 ,0
Exp/Cntr=0.3,0.1