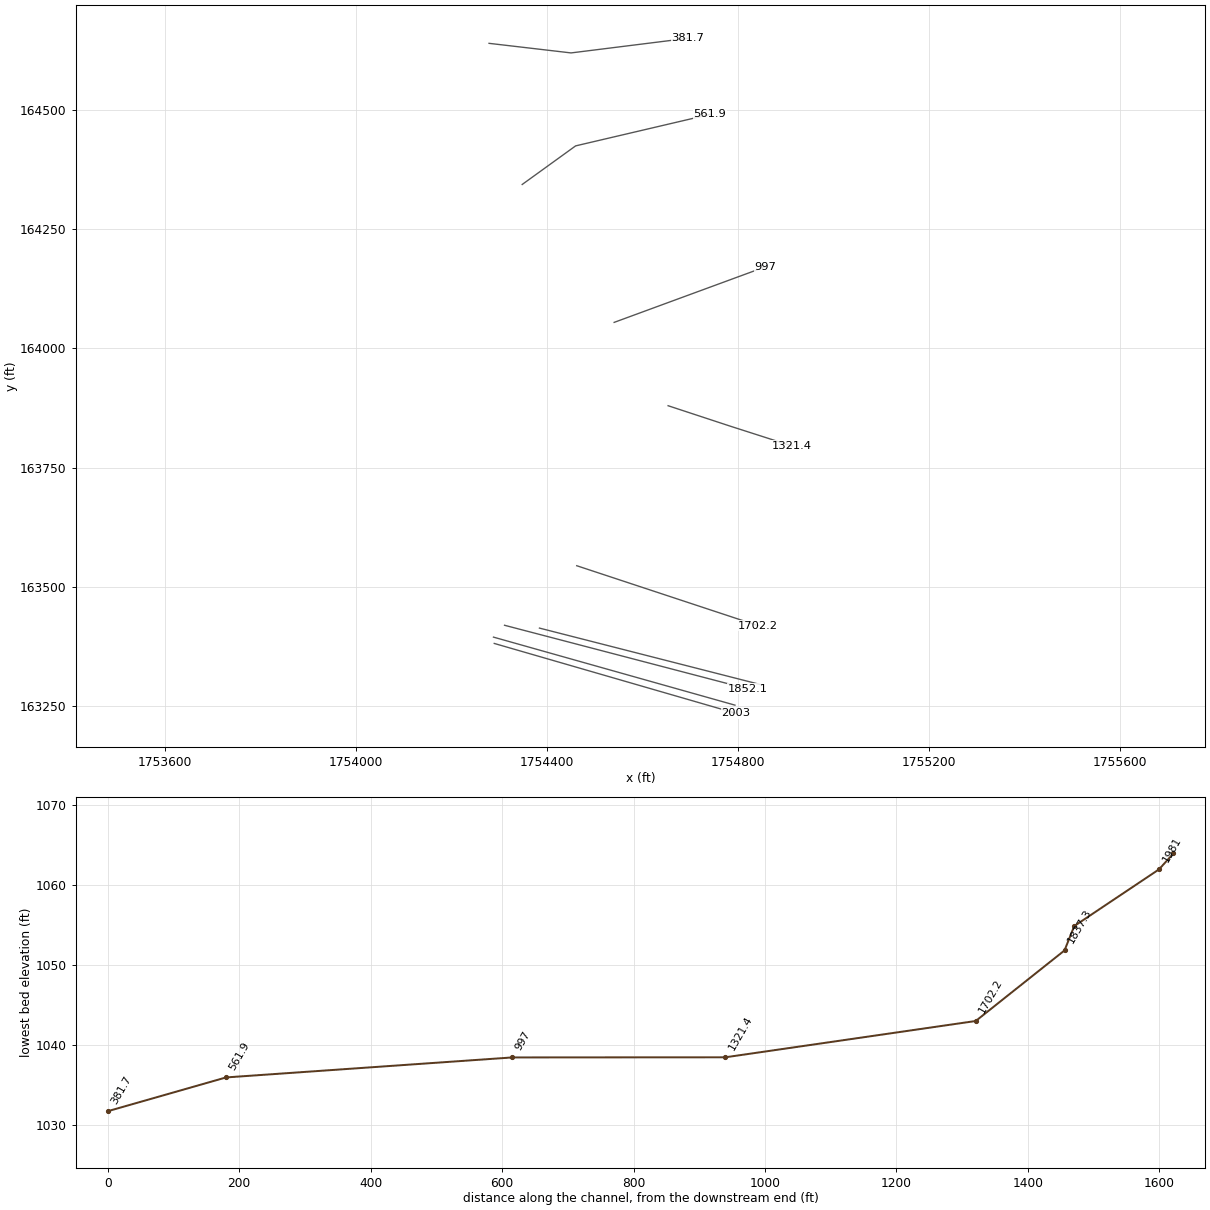
HEC-RAS study Clear Fork A.prj: Clear Fork A

--- Clear Fork A.g01 (geometry) --- (continued)

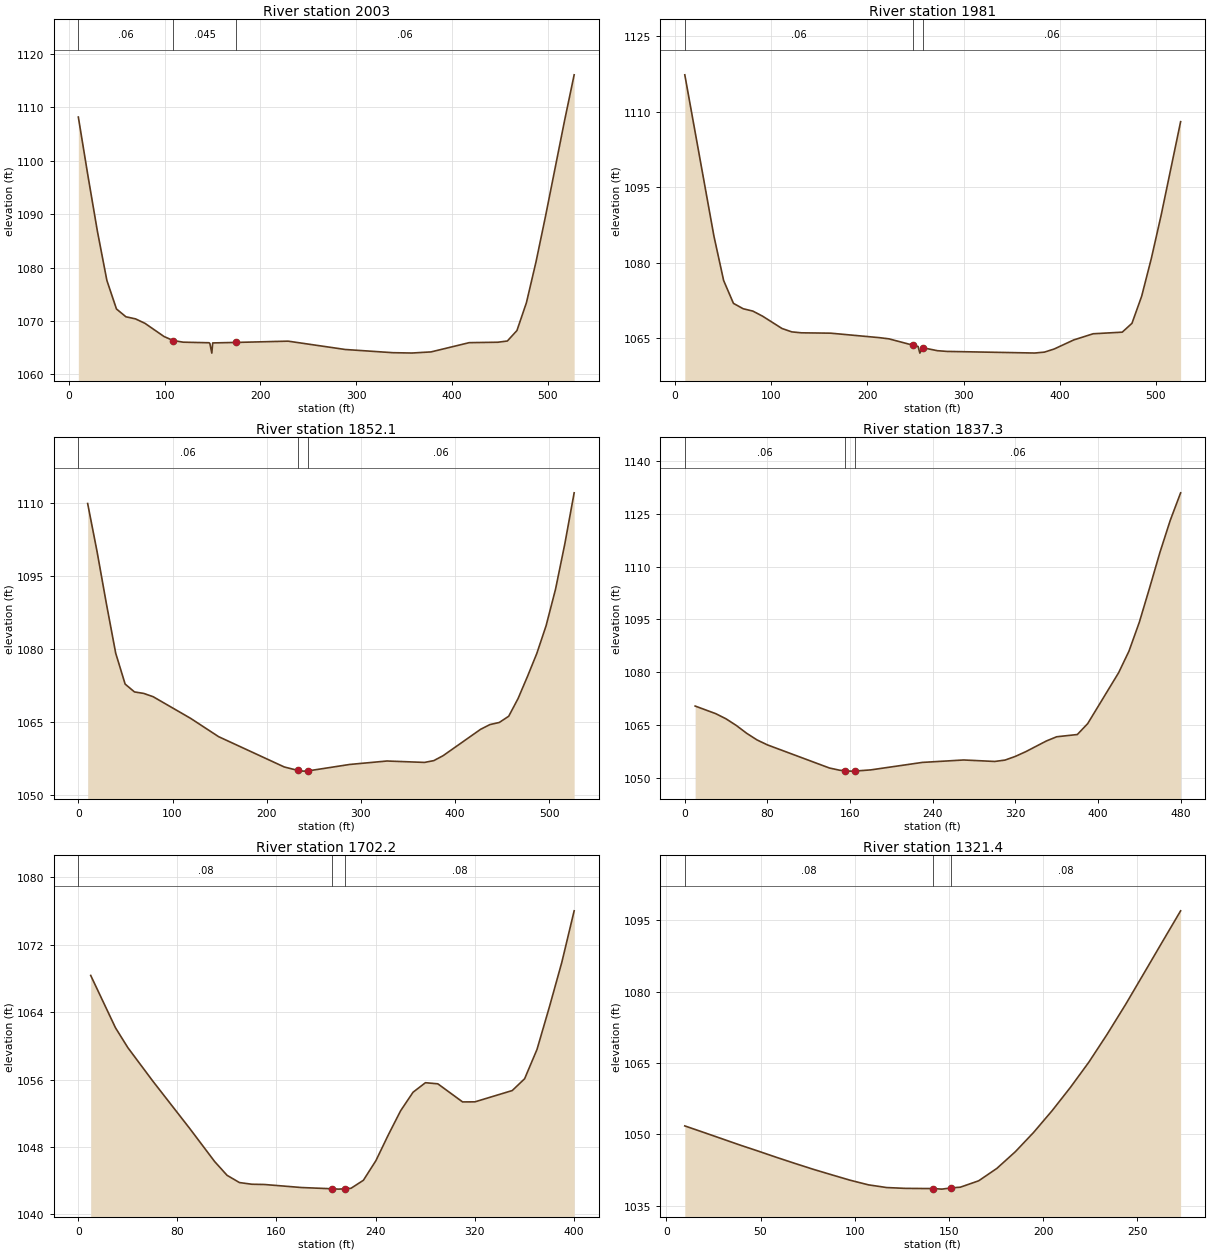
Type RM Length L Ch R = 1 ,2003    ,14.9,22,107.2
XS GIS Cut Line= 2
     1754289.233      163381.875     1754795.853      163235.353
#Sta/Elev= 30
      10 1108.17    19.9 1097.32    29.9 1086.79    39.8 1077.58    49.8 1072.24
    59.7 1070.78    69.7 1070.39    79.6 1069.55    99.5 1067.08     1091066.339
   119.4 1066.03  146.42 1065.92  147.27 1065.78   149.3 1063.98  150.22 1065.89
     1751065.984   228.9 1066.22   288.6 1064.66   338.3 1064.06   358.2    1064
   378.1 1064.21   417.9 1065.94   447.8 1066.02   457.7 1066.25   467.7 1068.21
   477.6 1073.42   487.6 1081.07   497.5 1089.59   517.4 1107.51   527.4 1116.07
#Mann= 3 , 0 , 0
      10     .06       0     109    .045       0     175     .06       0
Bank Sta=109,175
XS Rating Curve= 0 ,0
Exp/Cntr=0.3,0.1

Type RM Length L Ch R = 1 ,1981    ,57.8,128.9,37.7
XS GIS Cut Line= 2
     1754287.577       163395.12     1754793.541      163252.599
#Sta/Elev= 30
    10.1 1117.34    40.4 1085.25    50.5 1076.42    60.7 1071.88    70.8 1070.81
    80.9 1070.34      91 1069.33   111.2 1066.88   121.3 1066.21   131.4 1066.02
   161.7 1065.95   212.3 1065.06   222.4 1064.82   247.7 1063.54   252.7  1063.3
  254.53 1061.98   257.7 1063.05   272.9 1062.46     283 1062.32     374    1062
   384.1 1062.18   394.2  1062.8   414.5  1064.6   434.7 1065.83     465 1066.15
   475.1 1067.91   485.2 1073.31   495.3 1080.86   505.4 1089.38   525.7 1108.02
#Mann= 3 , 0 , 0
    10.1     .06       0   247.7    .045       0   257.7     .06       0
Bank Sta=247.7,257.7
XS Rating Curve= 0 ,0
Exp/Cntr=0.3,0.1

Type RM Length L Ch R = 1 ,1852.1  ,92.3,14.8,14.9
XS GIS Cut Line= 2
     1754310.756      163419.955     1754820.148      163286.742
#Sta/Elev= 30
     9.9 1109.89    19.9 1100.01    29.8  1089.3    39.7 1079.12    49.7 1072.78
    59.6 1071.17    69.5 1070.86    79.5 1070.18   119.2 1065.74     149 1061.97
   218.6 1055.75   233.4 1055.02   238.4 1054.89   243.4 1054.92   288.1 1056.26
   327.8 1056.97   367.6 1056.68   377.5 1057.05   387.4 1058.07   427.2 1063.49
   437.1 1064.46     447 1064.89     457 1066.17   466.9 1069.79   476.9 1074.33
   486.8 1079.05   496.7 1084.78   506.7 1092.26   516.6 1101.61   526.5 1112.09
#Mann= 3 , 0 , 0
       0     .06       0   233.4    .045       0   243.4     .06       0
Bank Sta=233.4,243.4
XS Rating Curve= 0 ,0
Exp/Cntr=0.3,0.1

Type RM Length L Ch R = 1 ,1837.3  ,136.7,135.1,133.5
XS GIS Cut Line= 2
     1754383.924      163414.045     1754849.003      163295.229
#Sta/Elev= 30
      10 1070.35      30 1068.18      40  1066.7      50  1064.8      60 1062.58
      70  1060.7      80  1059.3     140 1052.73     150 1052.09     155 1051.96
     160 1051.84     165 1051.87     180 1052.19     230 1054.32     270 1055.01
     300 1054.59     310 1054.98     320 1056.03     330 1057.36     350 1060.41
     360 1061.61     380 1062.25     390 1065.34     420 1079.84     430 1085.97
     440 1094.17     450 1103.99     460 1114.08     470  1123.2     480 1130.99
#Mann= 3 , 0 , 0
       0     .06       0     155    .045       0     165     .06       0
Bank Sta=155,165
XS Rating Curve= 0 ,0
Exp/Cntr=0.3,0.1

Type RM Length L Ch R = 1 ,1702.2  ,380.8,380.8,381
XS GIS Cut Line= 2
     1754462.003      163544.742     1754842.214      163419.137
#Sta/Elev= 30
      10 1068.37      30 1062.16      40  1059.8    60.1 1055.84    90.1 1050.18
   110.1 1046.28   120.1 1044.65   130.1 1043.79   140.1 1043.59   150.2 1043.56
   180.2  1043.2   205.2 1043.05   210.2 1043.01   215.2 1043.06   220.2 1043.11
   230.2 1044.06   240.3 1046.39   250.3 1049.44   260.3 1052.32   270.3 1054.51
   280.3 1055.64   290.3 1055.51   310.3 1053.36   320.3 1053.37   350.4 1054.71
   360.4 1056.11   370.4 1059.59   380.4 1064.63   390.4 1069.91   400.4 1076.04
#Mann= 3 , 0 , 0
       0     .08       0   205.2    .045       0   215.2     .08       0
Bank Sta=205.2,215.2
XS Rating Curve= 0 ,0
Exp/Cntr=0.3,0.1

Type RM Length L Ch R = 1 ,1321.4  ,311.4,324.5,337.4
XS GIS Cut Line= 3
     1754653.479      163879.966     1754783.145      163837.302
     1754913.121      163795.611
#Sta/Elev= 30
     9.8 1051.76    19.5 1050.44    29.3 1049.09      39 1047.75    48.8 1046.46
    58.5 1045.15    68.3 1043.87      78 1042.64    87.8 1041.48    97.5 1040.35
   107.3 1039.37     117  1038.8   126.8 1038.63   136.5  1038.6   141.3  1038.6
  146.29 1038.47   151.3 1038.74     156 1038.87   165.8 1040.22   175.5 1042.84
   185.3 1046.35     195 1050.41   204.8 1054.97   214.5 1059.86   224.3 1065.17
     234 1071.03   243.8  1077.3   253.5 1083.83   263.3 1090.46     273 1096.98
#Mann= 3 , 0 , 0
     9.8     .08       0   141.3    .045       0   151.3     .08       0
Bank Sta=141.3,151.3
XS Rating Curve= 0 ,0
Exp/Cntr=0.3,0.1

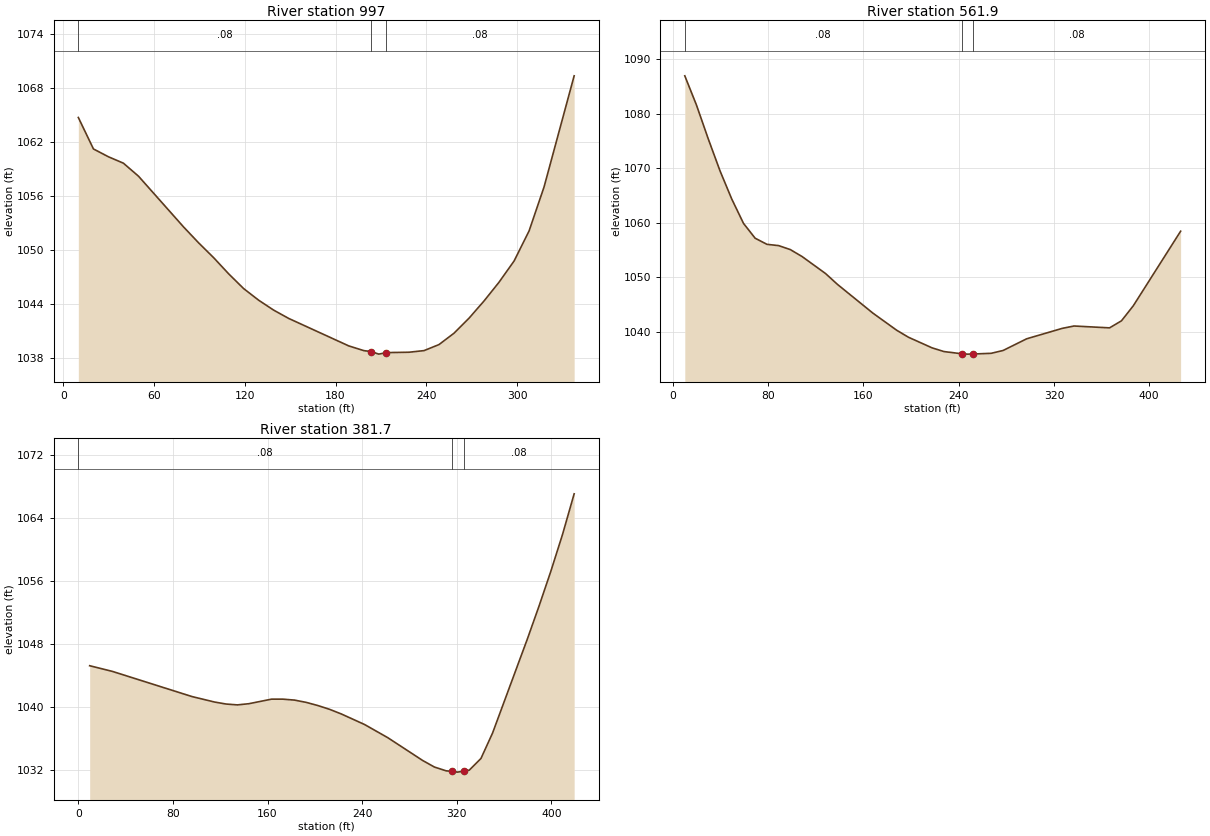
Type RM Length L Ch R = 1 ,997     ,437,435.1,432.9
XS GIS Cut Line= 2
     1754540.404       164054.57      1754857.49      164171.072
#Sta/Elev= 29
     9.9 1064.76    19.9 1061.26    29.8 1060.39    39.7 1059.68    49.7 1058.23
    79.5 1052.59    89.4 1050.83    99.4 1049.17   109.3 1047.38   119.2 1045.74
   129.2 1044.44   139.1 1043.34     149 1042.42   188.8 1039.36   198.7 1038.84
   203.6 1038.73   208.6 1038.45   213.6 1038.62   228.5 1038.66   238.5 1038.84
   248.4 1039.51   258.3 1040.77   268.3 1042.45   278.2 1044.36   288.1 1046.44
   298.1 1048.81     308 1052.15   317.9 1057.04   337.8 1069.39
#Mann= 3 , 0 , 0
     9.9     .08       0   203.6    .045       0   213.6     .08       0
Bank Sta=203.6,213.6
XS Rating Curve= 0 ,0
Exp/Cntr=0.3,0.1

Type RM Length L Ch R = 1 ,561.9   ,182.5,180.2,178.3
XS GIS Cut Line= 3
     1754347.752      164343.548     1754459.711      164424.398
     1754740.372      164490.177
#Sta/Elev= 30
     9.9 1086.92    19.7 1081.57    29.6 1075.38    39.5 1069.51    49.3 1064.38
    59.2  1059.9      69 1057.18    78.9 1056.06    88.8 1055.82    98.6 1055.09
   108.5 1053.81   128.2  1050.7   138.1 1048.73   167.9 1043.46   187.8 1040.34
   197.7 1039.05   217.6  1037.1   227.6 1036.42   242.4 1036.02   247.4 1035.95
   252.4 1035.97   267.3  1036.1   277.3 1036.62   297.1 1038.76     327 1040.67
   336.9  1041.1   366.7 1040.76   376.7 1042.05   386.6 1044.79   426.4 1058.46
#Mann= 3 , 0 , 0
     9.9     .08       0   242.4    .045       0   252.4     .08       0
Bank Sta=242.4,252.4
XS Rating Curve= 0 ,0
Exp/Cntr=0.3,0.1

Type RM Length L Ch R = 1 ,381.7   ,369.5,381.7,393.8
XS GIS Cut Line= 3
     1754278.308      164639.247     1754450.121      164619.178
     1754694.543       164649.73
#Sta/Elev= 30
     9.6 1045.25    28.8 1044.53    96.1 1041.33   115.3 1040.63   124.9 1040.38
   134.5 1040.27   144.2 1040.42   163.4    1041     173    1041   182.8 1040.88
   192.7 1040.59   202.5 1040.19   212.4 1039.71   222.2 1039.13     242 1037.78
   261.7  1036.1   291.2  1033.2   301.1 1032.37   310.9 1031.89   315.8 1031.81
   320.8 1031.72   325.8 1031.85   330.6 1031.97   340.5 1033.46   350.3 1036.69
   379.9 1048.72   389.7 1052.88   399.6 1057.27   409.5 1061.96   419.3 1067.11
#Mann= 3 , 0 , 0
       0     .08       0   315.8    .045       0   325.8     .08       0
Bank Sta=315.8,325.8
XS Rating Curve= 0 ,0
Exp/Cntr=0.3,0.1

Chan Stop Cuts=-1
Use User Specified Reach Order=0